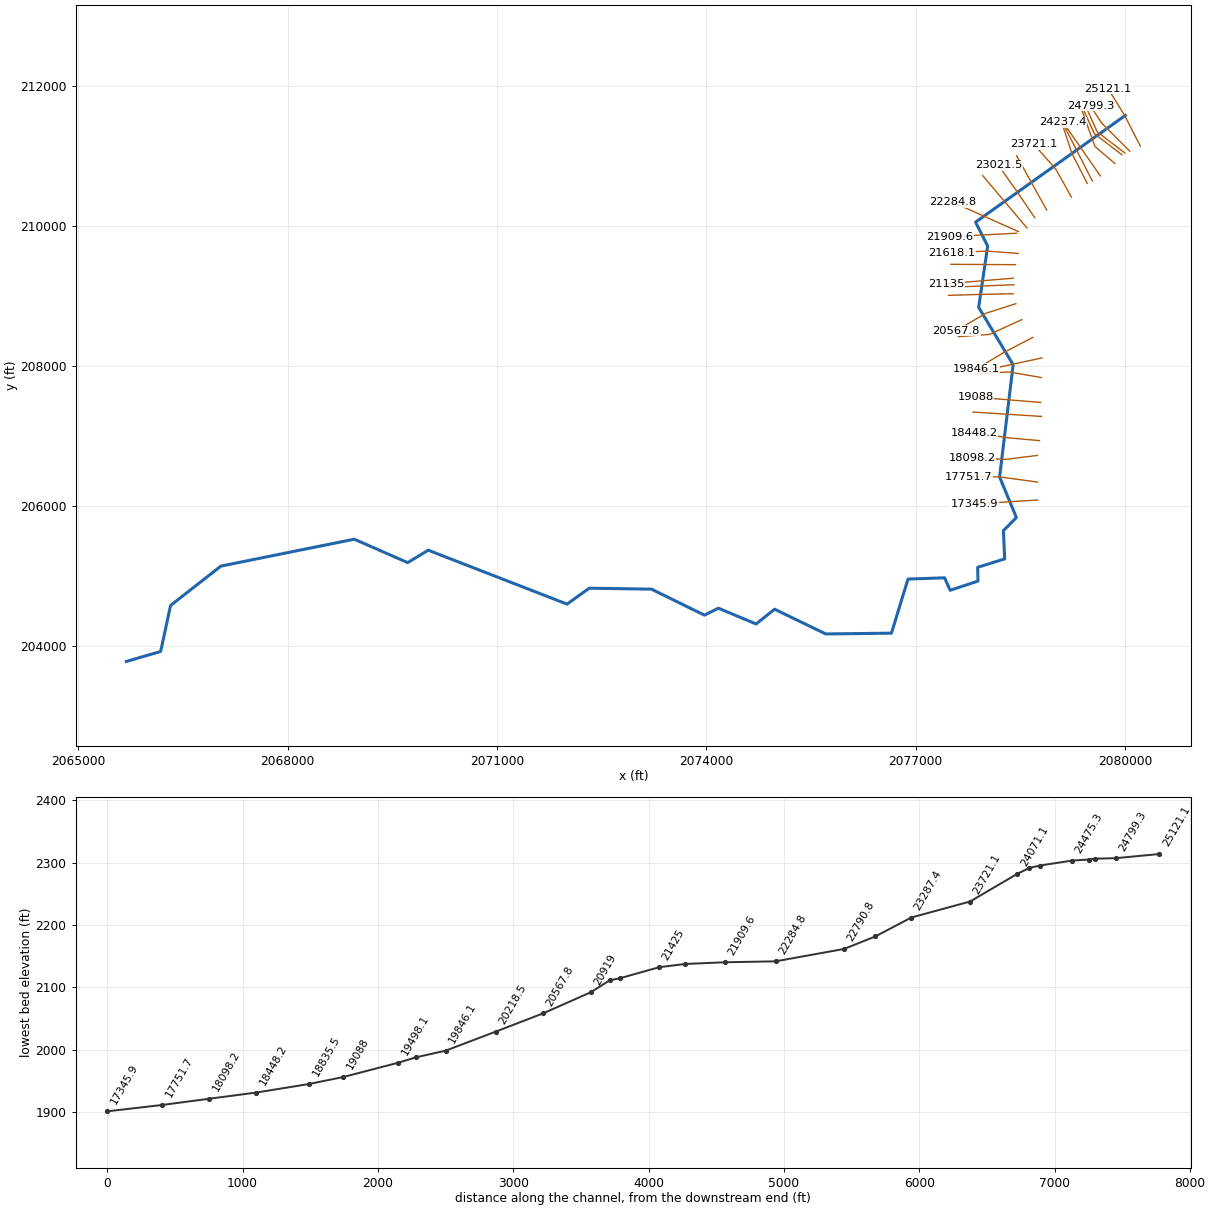
--- LAURELCK1.prj (project) ---

Proj Title=LAURELCK1
Current Plan=p01
Default Exp/Contr=0,0
English Units
Geom File=g01
Flow File=f01
Plan File=p01
BEGIN DESCRIPTION:
END DESCRIPTION:
DSS Export Rating Curves= 0
DSS Export Rating Curve Sorted= 0
DSS Export Volume Flow Curves= 0
DXF OffsetX= 0
DXF OffsetY= 0
DXF ScaleX= 0
DXF ScaleY= 0

--- LAURELCK1.p01 (plan) ---

Plan Title=Floodplain
Program Version=4.00
Geom File=g01
Flow File=f01
K Sum by GR=0
Std Step Tol=0.01
Critical Tol=0.01
Num of Std Step Trials=20
Max Error Tol=0.3
Flow Tol Ratio=0.001
Split Flow NTrial=30
Split Flow Tol=0.02
Split Flow Ratio=0.02
Log Output Level=0
Friction Slope Method=1
Unsteady Friction Slope Method=2
Unsteady Bridges Friction Slope Method=1
Global Log Level=0
CheckData=False
Run HTab=0
Run UNet=0
Run PostProcess=0
UNET Theta=0
UNET Theta Warmup=0
UNET ZTol=0
UNET ZSATol=0
UNET MxIter=0
UNET MaxInSteps=0
UNET DtIC=0
UNET DtMin=0
UNET MaxCRTS=0
UNET WFStab=0
UNET SFStab=0
UNET WFX=0
UNET SFX=0
UNET DSS MLevel=0
UNET DZMax Abort=0
UNET Convert EG Bridges=0
UNET Use Existing IB Tables=0
UNET Froude Limit=0
UNET Froude Power=0
Write IC File=0
Echo Input=False
Echo Output=False
Write Detailed=0

--- LAURELCK1.f01 (steady flow) ---

Flow Title=2010 USGS WV Regression Equation
Program Version=5.03
Number of Profiles= 1
Profile Names=P100yr
River Rch & RM=LAURELCK1,Main            ,25121.1
 557.113
River Rch & RM=LAURELCK1,Main            ,22284.8
599.1803
River Rch & RM=LAURELCK1,Main            ,21909.6
1043.669
River Rch & RM=LAURELCK1,Main            ,19498.1
1130.797
River Rch & RM=LAURELCK1,Main            ,11551.2
1244.771
River Rch & RM=LAURELCK1,Main            ,7253.7
1371.153
River Rch & RM=LAURELCK1,Main            ,6281.8
1475.762
River Rch & RM=LAURELCK1,Main            ,4101.1
1638.715
River Rch & RM=LAURELCK1,Main            ,236.8
1815.779
Boundary for River Rch & Prof#=LAURELCK1,Main            , 1
Up Type= 0
Dn Type= 3
Dn Slope=0.00507
DSS Import GetInterval= 0
DSS Import GetPeak= 0
DSS Import FillOption= 0

--- LAURELCK1.g01 (geometry) ---

Geom Title=LiDAR
Program Version=4.10

River Reach=LAURELCK1       ,Main
Reach XY= 30
     2080008.125      211582.228     2077860.284      210056.214
     2078034.051      209713.836     2077904.885      208839.356
      2078399.19      208018.318     2078205.074      206414.209
     2078445.872      205835.129     2078259.789      205647.863
     2078277.831      205244.449     2077890.865      205123.992
     2077895.206      204927.377       2077495.9      204795.433
     2077416.473      204973.818     2076891.825      204955.843
     2076654.676      204182.705     2075713.348      204171.735
     2074980.004      204525.042     2074714.072      204314.298
     2074175.183      204539.299     2073973.099      204440.687
     2073213.735      204811.885     2072321.711       204825.41
     2072004.729      204597.909     2070014.603      205368.357
     2069720.332      205190.752     2068954.186      205525.648
     2067042.207      205141.274     2066321.251      204578.731
      2066178.76      203921.136     2065687.365      203778.869

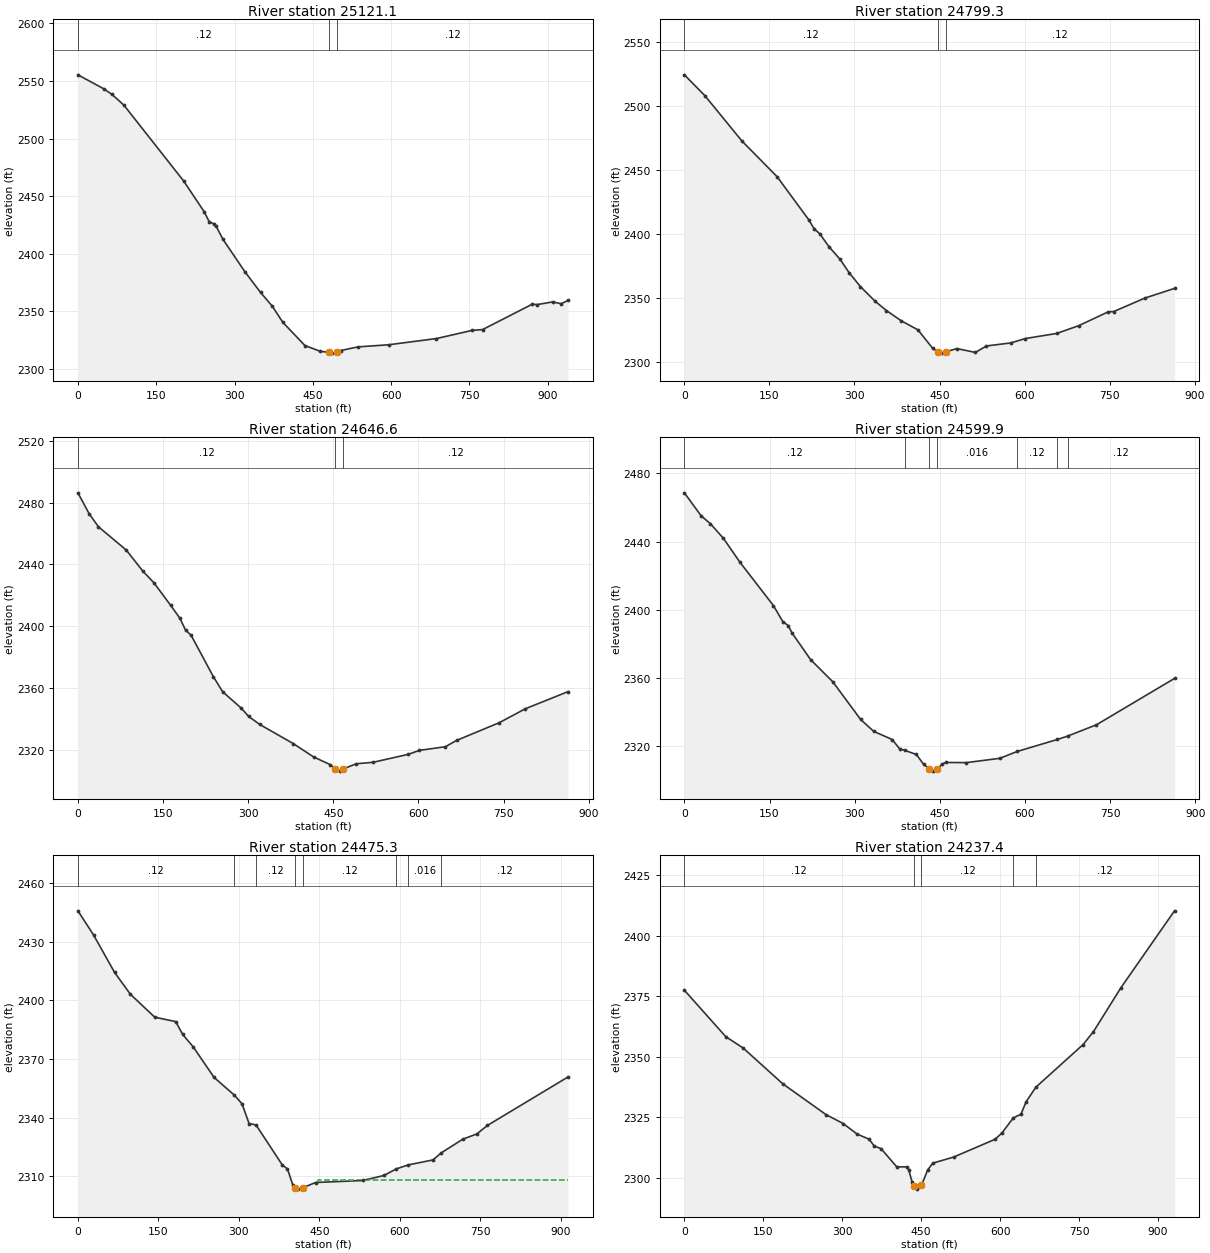
Type RM Length L Ch R = 1 ,25121.1 ,313.8,321.8,326.5
XS GIS Cut Line= 3
     2080221.584      211143.603     2079998.495      211580.258
     2079761.623       211961.18
#Sta/Elev= 30
       0 2555.33      49 2543.33    65.4 2538.29    88.3 2528.92   202.7 2463.12
   241.9 2436.53   251.7 2427.67   261.5 2425.87   264.8 2423.96   277.9 2412.57
   320.4 2384.14   349.8 2366.56   372.7  2354.4   392.3 2340.72   434.8 2320.48
   464.2 2315.46  481.642314.552   487.1 2313.88   496.9  2314.6   503.4  2316.1
   536.2 2319.29   595.1 2321.12   686.8 2326.52   755.6 2333.65   775.2  2334.3
   870.2 2356.31     880 2356.02   909.4  2358.3   925.8 2356.77   938.9 2359.58
#Mann= 3 ,-1 , 0
       0     .12       0  481.64    .045       0   496.9     .12       0
Bank Sta=481.64,496.9
XS Rating Curve= 0 ,0
Exp/Cntr=0.3,0.1

Type RM Length L Ch R = 1 ,24799.3 ,149,152.7,154.9
XS GIS Cut Line= 3
     2080070.904      211069.899      2079666.39      211474.413
     2079506.668      211719.205
#Sta/Elev= 30
       0 2524.49      36 2508.29   101.3 2472.91   163.4 2445.02     219 2411.53
   228.8 2404.28   238.6 2400.48     255 2390.31   274.6 2380.45   290.9 2369.79
   310.6  2359.1   336.7 2347.57   356.3 2340.47   382.5 2332.45   411.9 2325.39
     438 2310.93  446.732308.222   454.4 2307.21   460.9 2308.17   480.5 2310.78
   513.2 2307.75   532.8 2312.81   575.3 2315.14   601.3  2318.6   656.5 2322.57
   695.5 2328.64   747.4 2339.42   757.2 2339.67   812.4 2350.24   864.4 2357.75
#Mann= 3 ,-1 , 0
       0     .12       0  446.73    .045       0   460.9     .12       0
Bank Sta=446.73,460.9
XS Rating Curve= 0 ,0
Exp/Cntr=0.3,0.1

Type RM Length L Ch R = 1 ,24646.6 ,47,46.7,46.6
XS GIS Cut Line= 3
     2079998.855      211045.594      2079603.89      211347.243
     2079453.066      211681.445
#Sta/Elev= 30
       0 2486.28    19.6 2472.88      36 2464.38      85 2449.35   114.4 2435.69
     134  2428.1   163.5  2413.5   179.8 2405.14   189.6 2397.58   199.4 2394.22
   238.7 2367.41     255 2357.71   287.7 2347.14   300.8 2341.74   320.4 2336.54
   379.3 2324.22   415.2 2315.58   444.7 2310.56  453.072307.797     461 2306.39
   467.6 2307.81   490.4 2311.15   519.9 2312.09   582.1 2317.24   601.7 2319.79
   647.6 2322.18   667.2 2326.24   742.5 2337.71   788.3  2346.7   863.6 2357.77
#Mann= 3 ,-1 , 0
       0     .12       0  453.07    .045       0   467.6     .12       0
Bank Sta=453.07,467.6
XS Rating Curve= 0 ,0
Exp/Cntr=0.3,0.1

Type RM Length L Ch R = 1 ,24599.9 ,137.2,124.5,109.6
XS GIS Cut Line= 3
     2079957.623      211019.552     2079562.658      211321.201
     2079411.833      211655.403
#Sta/Elev= 30
       0 2468.62    29.4 2455.15    45.8 2450.49    68.7  2441.9    98.1 2427.73
   156.9 2402.34   173.3 2392.99   183.1 2390.56   189.6  2386.3   222.3 2370.62
   261.6 2357.52   310.6  2335.4   333.5 2328.45   366.2 2323.62   379.3 2318.16
  388.112317.296   408.7 2314.84   421.8 2308.96   431.6 2306.34   438.1 2305.05
   445.9  2306.3   454.5 2309.37     461 2310.14     497 2310.05   555.9 2312.59
  586.452316.608  657.222323.656  675.122325.628   726.1 2332.29   863.6 2359.54
#Mann= 7 ,-1 , 0
       0     .12       0  388.11    .016       0   431.6    .045       0
   445.9    .016       0  586.45     .12       0  657.22     .06       0
  675.12     .12       0
Bank Sta=431.6,445.9
XS Rating Curve= 0 ,0
Exp/Cntr=0.3,0.1

Type RM Length L Ch R = 1 ,24475.3 ,220,237.9,243.1
XS GIS Cut Line= 3
     2079857.145      210894.624     2079572.423       211137.68
     2079388.395      211644.624
#Sta/Elev= 30
       0 2445.85    29.3 2433.43    68.4 2414.28    97.7 2403.17   143.2 2391.39
   182.3 2389.13   195.3 2382.54   214.8 2376.25   253.9 2360.52  291.512351.509
     306 2347.01     319 2336.95  332.042336.202   380.9 2315.78   390.7 2313.67
   400.5 2305.56   405.12304.064   410.3 2303.35   420.1 2304.15     443 2306.74
   531.2 2307.77   570.5 2310.34  593.232313.681  615.982315.771     662  2318.3
   677.3 2321.92   717.6 2328.94   743.7  2331.6   763.3 2335.95   913.7 2360.79
#Mann= 8 ,-1 , 0
       0     .12       0  291.51    .016       0  332.04     .12       0
   405.1    .045       0   420.1     .12       0  593.23     .06       0
  615.98    .016       0   677.3     .12       0
#XS Ineff= 2 , 0
                          447.87         2308.14
Permanent Ineff=
       F       F
Bank Sta=405.1,420.1
XS Rating Curve= 0 ,0
Exp/Cntr=0.3,0.1

Type RM Length L Ch R = 1 ,24237.4 ,81.7,78.7,76
XS GIS Cut Line= 2
     2079648.621        210717.9     2079115.852      211481.789
#Sta/Elev= 30
       0 2377.51    78.7 2358.33   111.5 2353.69   186.9 2338.89   268.9  2326.2
   301.7 2322.48   327.9 2318.17   350.9 2316.01   360.7 2313.22   373.8  2312.1
   403.4 2304.62     423 2304.58   426.3 2303.38   432.9 2298.15   436.2 2296.82
   442.7  2295.4   450.5 2296.96   462.4 2303.37   472.2 2306.14   511.6 2308.63
   590.3 2315.97   603.4 2318.58  625.122324.844   639.5  2326.3   649.3 2331.46
  667.85 2337.48   757.5 2355.07   777.2 2360.38   829.7 2378.63   931.3  2410.3
#Mann= 5 ,-1 , 0
       0     .12       0   436.2    .045       0   450.5     .12       0
  625.12    .016       0  667.85     .12       0
Bank Sta=436.2,450.5
XS Rating Curve= 0 ,0
Exp/Cntr=0.3,0.1

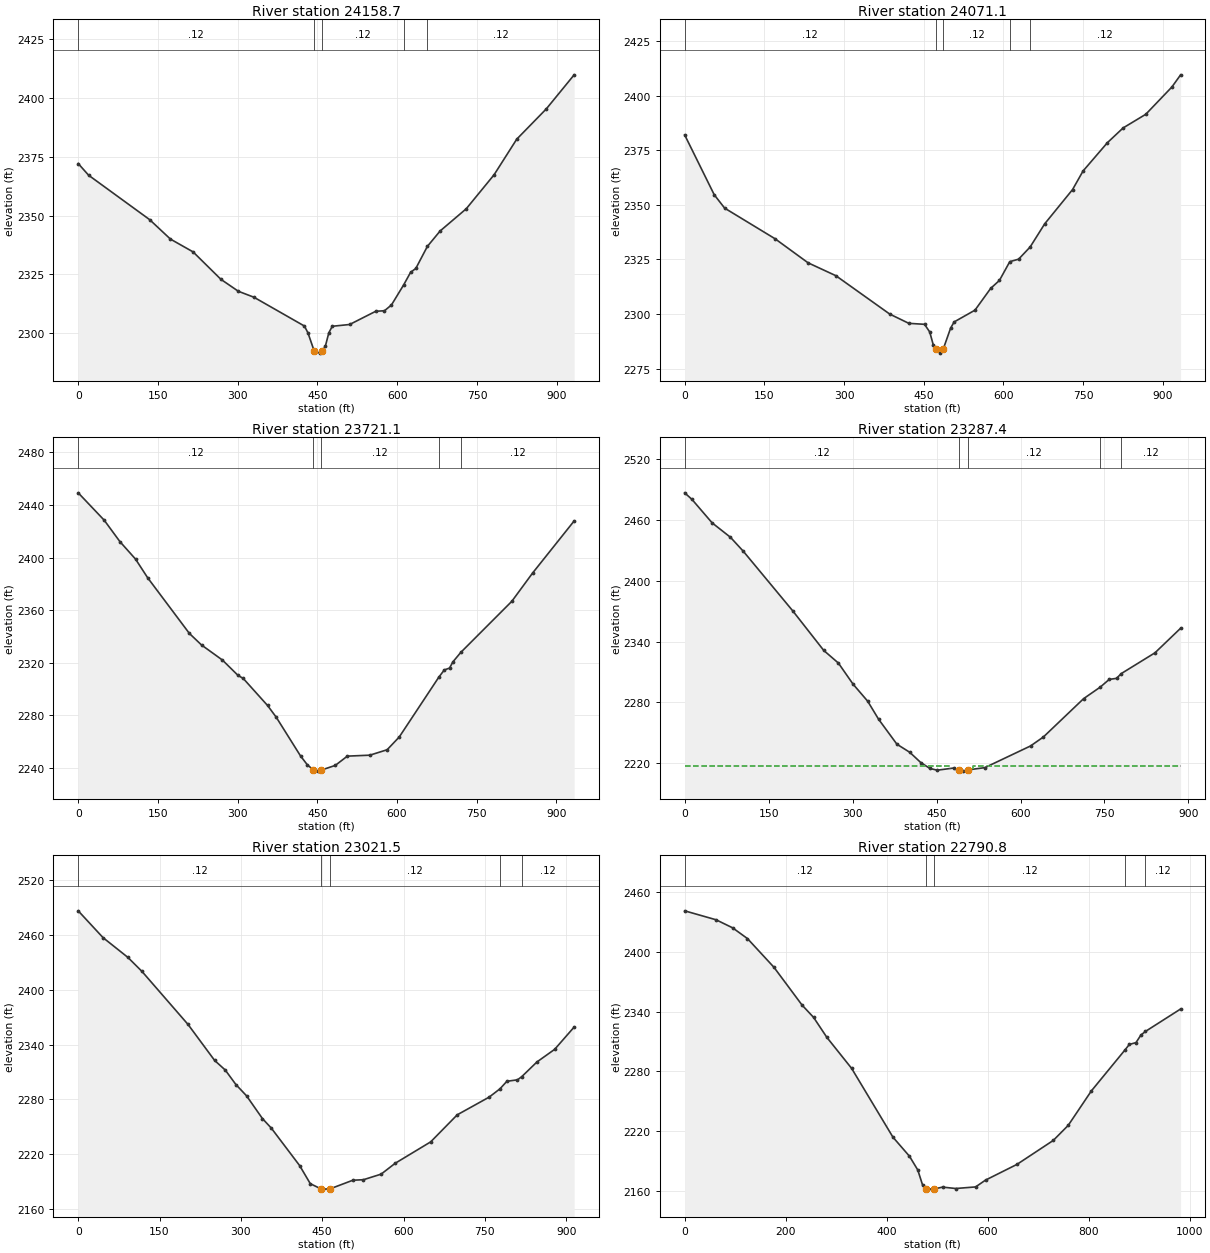
Type RM Length L Ch R = 1 ,24158.7 ,87.7,87.6,83.9
XS GIS Cut Line= 2
     2079533.603      210646.286     2079108.256      211476.364
#Sta/Elev= 30
       0 2372.15    19.6 2367.17   134.2  2348.3   173.4    2340     216 2334.55
   268.4 2322.86   301.1 2317.79   330.5 2315.24   425.4 2302.98     432 2300.11
  443.722292.411   454.9 2291.45  458.842292.432   464.7 2294.32   471.3 2300.09
   477.8 2302.88   510.5 2303.64   559.6 2309.27     576 2309.49   589.1 2311.95
  612.212320.549   625.1 2325.86   634.9 2327.49  656.65 2336.88   680.7 2343.46
   729.8 2352.91   782.2  2367.4   824.7 2382.52   880.4 2395.44   932.7 2409.92
#Mann= 5 ,-1 , 0
       0     .12       0  443.72    .045       0  458.84     .12       0
  612.21    .016       0  656.65     .12       0
Bank Sta=443.72,458.84
XS Rating Curve= 0 ,0
Exp/Cntr=0.3,0.1

Type RM Length L Ch R = 1 ,24071.1 ,347.2,350,358.1
XS GIS Cut Line= 3
     2079460.963      210609.795     2079241.783      211037.882
     2079099.679      211467.689
#Sta/Elev= 30
       0 2381.98    55.6 2354.61    75.2 2348.48   170.1 2334.46   232.3 2323.44
   284.6 2317.55   386.1 2299.97     422 2295.74   451.5  2295.3   461.3  2291.8
   467.8 2286.04  472.332283.801   480.9 2282.11  486.592283.865   500.6 2293.54
   507.2 2296.38   546.5 2301.78   576.1 2311.76   592.5 2315.38     6122323.971
   628.6 2325.11   650.32330.678   677.8 2341.31   730.2 2356.97   749.9 2365.45
   795.8 2378.43   825.4 2385.18     868 2391.42   917.2 2403.92   933.6 2409.48
#Mann= 5 ,-1 , 0
       0     .12       0  472.33    .045       0  486.59     .12       0
     612    .016       0   650.3     .12       0
Bank Sta=472.33,486.59
XS Rating Curve= 0 ,0
Exp/Cntr=0.3,0.1

Type RM Length L Ch R = 1 ,23721.1 ,431.8,433.7,427.4
XS GIS Cut Line= 3
      2079234.41      210414.019     2079014.639       210808.03
     2078695.918      211170.109
#Sta/Elev= 30
       0 2449.21      49 2428.37    78.5 2412.13   107.9 2398.84   130.8 2384.61
   209.2 2342.38   232.1 2333.57   271.4 2322.14   300.8 2310.47   310.6 2308.16
   356.4 2287.59   372.7  2278.7   418.5 2249.22   431.5  2242.4   442.62238.685
   451.2 2237.71   457.7 2238.54   483.8 2242.04   506.6 2249.11   548.9 2249.83
   581.5 2253.96   604.3 2263.67  678.712309.084   689.1 2314.61   698.9 2316.02
   705.4  2320.8  720.082327.919   816.2 2366.78   855.3 2388.26   933.5 2427.85
#Mann= 5 ,-1 , 0
       0     .12       0   442.6    .045       0   457.7     .12       0
  678.71    .016       0  720.08     .12       0
Bank Sta=442.6,457.7
XS Rating Curve= 0 ,0
Exp/Cntr=0.3,0.1

Type RM Length L Ch R = 1 ,23287.4 ,262.4,265.9,266.6
XS GIS Cut Line= 2
     2078879.715      210229.694     2078449.159      211003.999
#Sta/Elev= 30
       0 2486.96    13.1 2480.42      49 2457.31    81.7 2443.09   104.6 2429.34
   192.9  2370.5   248.5 2331.27   274.6 2318.83   300.8 2298.02   326.9 2281.19
   346.5 2263.29   379.2 2238.66   402.1 2230.71   421.7  2220.6   438.1 2214.75
   451.2 2213.03   480.6 2215.15   490.4 2213.22   496.9  2212.1   506.7 2213.39
   536.2 2215.53   617.9 2236.97   640.8  2245.8   712.7 2283.68   742.62295.163
   758.5 2302.71   771.5 2303.71  780.022308.456   840.2 2328.96     886 2353.23
#Mann= 5 ,-1 , 0
       0     .12       0   490.4    .045       0   506.7     .12       0
   742.6    .016       0  780.02     .12       0
#XS Ineff= 2 , 0
          473.35 2216.84  514.21         2216.76
Permanent Ineff=
       F       F
Bank Sta=490.4,506.7
XS Rating Curve= 0 ,0
Exp/Cntr=0.3,0.1

Type RM Length L Ch R = 1 ,23021.5 ,227.9,230.8,232.3
XS GIS Cut Line= 3
     2078708.569      210119.818     2078449.387      210500.609
     2078186.999       210871.06
#Sta/Elev= 30
       0 2486.56    45.7 2457.24    91.5 2435.62   117.6 2420.19   202.6 2362.08
   251.6  2322.7   271.2 2312.19   290.8 2296.31   310.4 2283.99   339.8    2259
   356.1  2248.6   408.4 2207.52     428 2187.74   447.6 2182.08   450.8 2181.78
   463.9 2181.96   506.4 2191.51     526 2192.09   558.6 2198.18   584.7 2210.14
     650 2233.53     699 2263.16   757.8 2282.52  777.792291.616   790.5 2299.88
   810.1 2301.48  818.052304.989     846 2321.06   878.7 2334.89   914.6 2359.27
#Mann= 5 ,-1 , 0
       0     .12       0   447.6    .045       0   463.9     .12       0
  777.79    .016       0  818.05     .12       0
Bank Sta=447.6,463.9
XS Rating Curve= 0 ,0
Exp/Cntr=0.3,0.1

Type RM Length L Ch R = 1 ,22790.8 ,485.5,506,511.7
XS GIS Cut Line= 2
     2078598.465      209972.749     2077963.048      210721.013
#Sta/Elev= 30
       0 2441.38    62.2 2432.38    94.9  2424.3   124.3 2413.49   176.7 2384.68
   232.3 2346.72   255.2 2334.29   281.4 2314.28   330.5 2283.07   412.3 2213.95
     445  2194.8   461.4 2181.04   471.2 2165.48   477.7  2162.1     481 2161.78
   494.1 2161.98   510.5  2163.8   536.6 2162.41   575.9    2164   595.5 2170.84
   657.7 2186.61   729.7 2210.74   759.2 2225.83     805 2260.43  871.282301.435
   880.2 2307.15   893.3 2308.96   903.1 2316.58  912.162320.247   981.7 2342.76
#Mann= 5 ,-1 , 0
       0     .12       0   477.7    .045       0   494.1     .12       0
  871.28    .016       0  912.16     .12       0
Bank Sta=477.7,494.1
XS Rating Curve= 0 ,0
Exp/Cntr=0.3,0.1

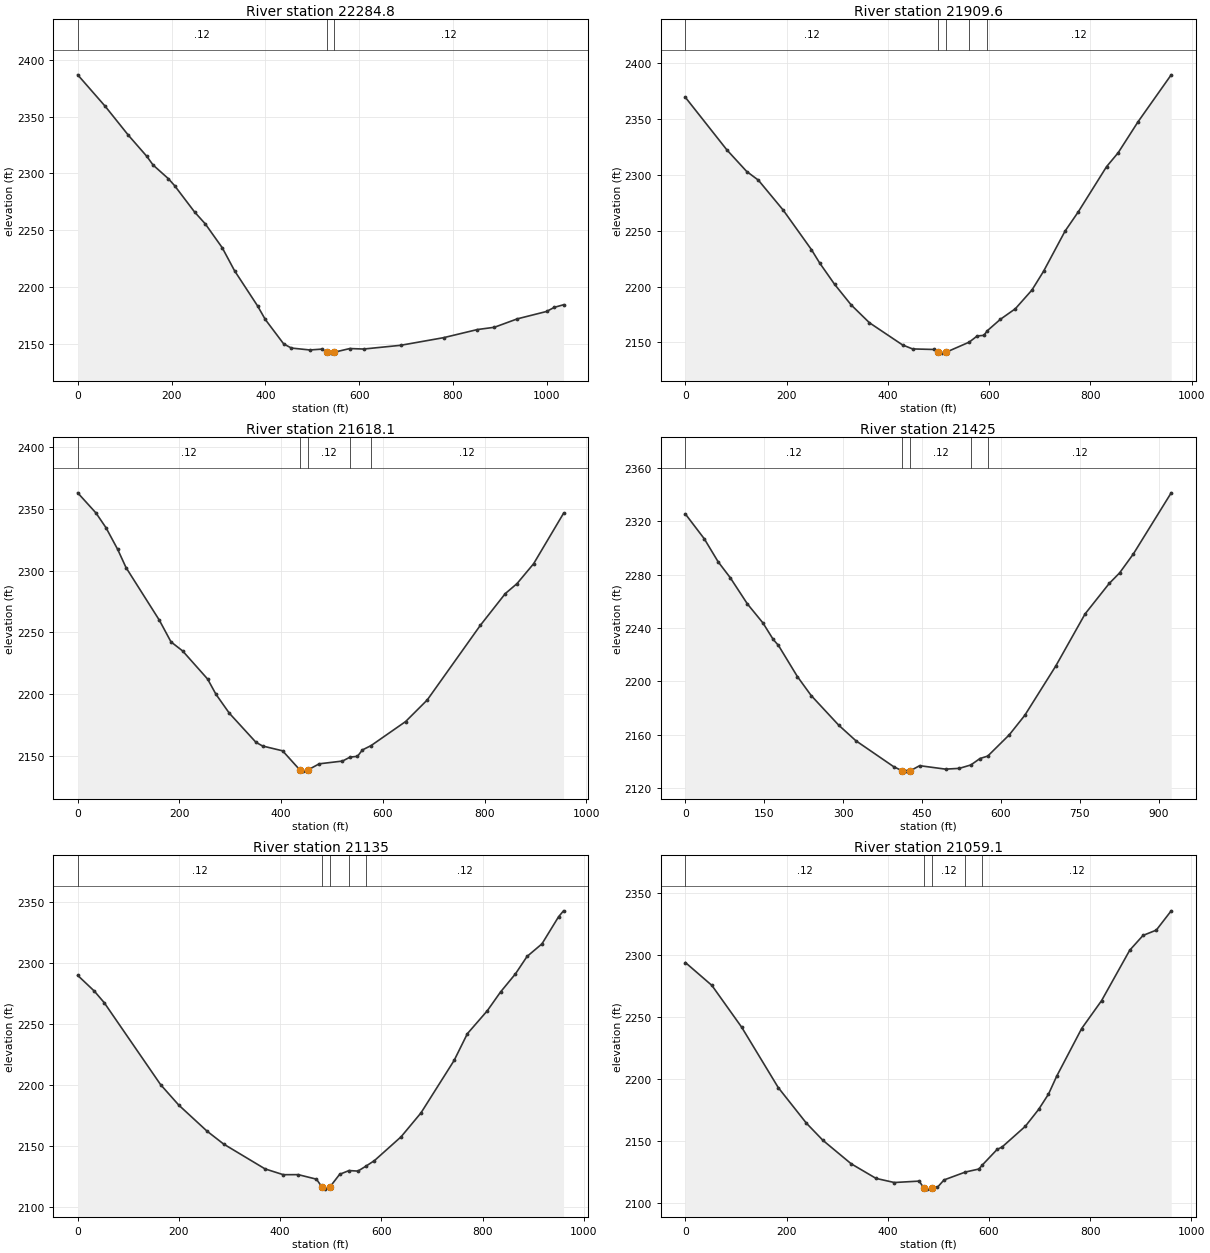
Type RM Length L Ch R = 1 ,22284.8 ,364.4,375.2,379.1
XS GIS Cut Line= 2
     2078476.511       209920.14     2077530.669      210342.595
#Sta/Elev= 30
       0 2386.65      59  2358.8   108.2 2333.45   147.5  2314.9   160.6 2307.39
   193.4 2295.29   206.5 2289.27   249.1 2266.09   272.1 2255.54   308.2  2234.6
   334.4 2214.41   383.5 2183.46   399.9 2171.57   439.3 2149.98   455.7 2146.38
     495 2144.69   521.2 2145.46   531.1 2142.58   540.9 2141.92  546.262142.636
   580.2 2145.95   609.7 2145.52   688.4 2148.79   780.2 2155.51   852.3 2162.66
   888.4 2164.65   937.6 2172.09   999.8 2178.56  1016.2 2182.18  1035.9 2184.45
#Mann= 3 ,-1 , 0
       0     .12       0   531.1    .045       0  546.26     .12       0
Bank Sta=531.1,546.26
XS Rating Curve= 0 ,0
Exp/Cntr=0.3,0.1

Type RM Length L Ch R = 1 ,21909.6 ,292.3,291.5,290.4
XS GIS Cut Line= 2
     2078449.159      209898.097     2077490.826      209849.486
#Sta/Elev= 30
       0 2369.47    81.9 2322.44   121.2 2303.04   144.1 2295.34   193.2 2268.49
   248.9 2233.16   265.3 2221.09   294.8    2202   327.5 2183.57   363.5 2167.64
     429 2147.74   448.7  2144.2   491.2 2143.69  499.542141.078   507.6 2140.43
   514.2 2141.09  560.682150.292   576.4 2155.81   589.5 2156.33  596.682160.615
   622.2 2170.73   651.7 2180.16   684.5 2196.91   707.4 2213.66     750 2249.75
   776.2 2267.04   831.8 2307.33   854.8 2319.84   894.1  2347.6   959.6 2389.63
#Mann= 5 ,-1 , 0
       0     .12       0  499.54    .045       0   514.2     .12       0
  560.68    .016       0  596.68     .12       0
Bank Sta=499.54,514.2
XS Rating Curve= 0 ,0
Exp/Cntr=0.3,0.1

Type RM Length L Ch R = 1 ,21618.1 ,191.2,193,191.7
XS GIS Cut Line= 3
     2078472.722       209608.69     2078028.671      209642.848
     2077519.495      209621.784
#Sta/Elev= 30
       0 2362.98      36 2346.62    55.7 2334.69    78.6 2317.19      95 2302.46
   160.5 2259.87   183.4 2242.32   206.3 2234.98   255.4 2212.22   271.8 2199.89
     298 2184.61   350.4 2161.03   363.5 2158.03   402.8 2154.13  436.942138.564
   442.1  2137.7   451.9 2138.53   474.8 2143.62   520.5 2145.85  535.642149.085
   549.9 2149.65   559.7 2154.87   576.82158.399   644.6 2177.84   687.1 2195.31
   791.6 2255.79   840.6 2281.45   863.5 2289.46   896.2 2305.58     955 2346.38
#Mann= 5 ,-1 , 0
       0     .12       0  436.94    .045       0   451.9     .12       0
  535.64    .016       0   576.8     .12       0
Bank Sta=436.94,451.9
XS Rating Curve= 0 ,0
Exp/Cntr=0.3,0.1

Type RM Length L Ch R = 1 ,21425   ,287.2,290.1,291.2
XS GIS Cut Line= 2
     2078431.798      209448.444     2077508.187      209453.652
#Sta/Elev= 30
       0  2325.4      36 2306.75    62.2 2289.59    85.2 2277.67   117.9 2257.95
   147.4  2243.7     167  2231.3   176.9 2226.84   212.9 2203.48   239.1 2189.25
   291.5    2167   324.2 2155.31   396.3 2135.79   412.7 2132.69   419.2 2132.54
  427.412132.787   445.4 2136.63   494.6 2134.03   520.8 2134.62  542.672137.167
   560.1    2142  574.862143.839   615.8  2159.8   645.2 2174.38   704.2 2211.43
   759.9 2250.49   805.7 2273.29   825.4 2281.17   851.6 2295.42   923.6 2341.28
#Mann= 5 ,-1 , 0
       0     .12       0   412.7    .045       0  427.41     .12       0
  542.67    .016       0  574.86     .12       0
Bank Sta=412.7,427.41
XS Rating Curve= 0 ,0
Exp/Cntr=0.3,0.1

Type RM Length L Ch R = 1 ,21135   ,77.2,75.9,74.7
XS GIS Cut Line= 2
     2078400.548      209255.736     2077443.951      209175.874
#Sta/Elev= 30
       0 2290.09    32.8 2277.21    52.4  2267.7   163.8  2200.5   199.8  2183.7
   255.5  2162.4   288.3 2151.82   370.2 2131.43   406.2 2126.68   435.7 2126.73
   471.8    2123  482.47 2116.65   488.2 2114.85     498 2116.48   517.6    2127
  536.072130.066   553.7 2129.64  569.752133.745   586.4 2138.27   638.9 2157.74
   678.2 2177.33   743.7 2220.33   769.9 2242.28   809.2 2261.04   835.4 2276.45
   864.9 2291.33   887.8 2305.58   917.3 2315.94   950.1 2338.12   959.9 2343.01
#Mann= 5 ,-1 , 0
       0     .12       0  482.47    .045       0     498     .12       0
  536.07    .016       0  569.75     .12       0
Bank Sta=482.47,498
XS Rating Curve= 0 ,0
Exp/Cntr=0.3,0.1

Type RM Length L Ch R = 1 ,21059.1 ,137.8,140.1,138.2
XS GIS Cut Line= 2
     2078411.182      209161.913     2077451.546      209124.153
#Sta/Elev= 30
       0 2293.74    52.4 2275.32   111.4 2241.64   183.6 2193.16   239.3 2164.52
     272 2150.72   327.8 2131.88   376.9 2120.15     413 2116.84   462.2 2117.97
   471.52112.357   478.6 2111.52   488.4 2112.18   498.2 2112.98   511.3 2118.92
  553.662125.278   580.2 2127.68  586.912130.864   616.2 2143.42     626 2145.37
   671.9    2162   698.2 2175.56   717.8 2187.91   734.2 2202.48   783.4 2240.66
   822.7 2263.06   878.4 2303.64   904.7 2315.53   930.9 2319.79   960.4 2335.31
#Mann= 5 ,-1 , 0
       0     .12       0   471.5    .045       0   488.4     .12       0
  553.66    .016       0  586.91     .12       0
Bank Sta=471.5,488.4
XS Rating Curve= 0 ,0
Exp/Cntr=0.3,0.1

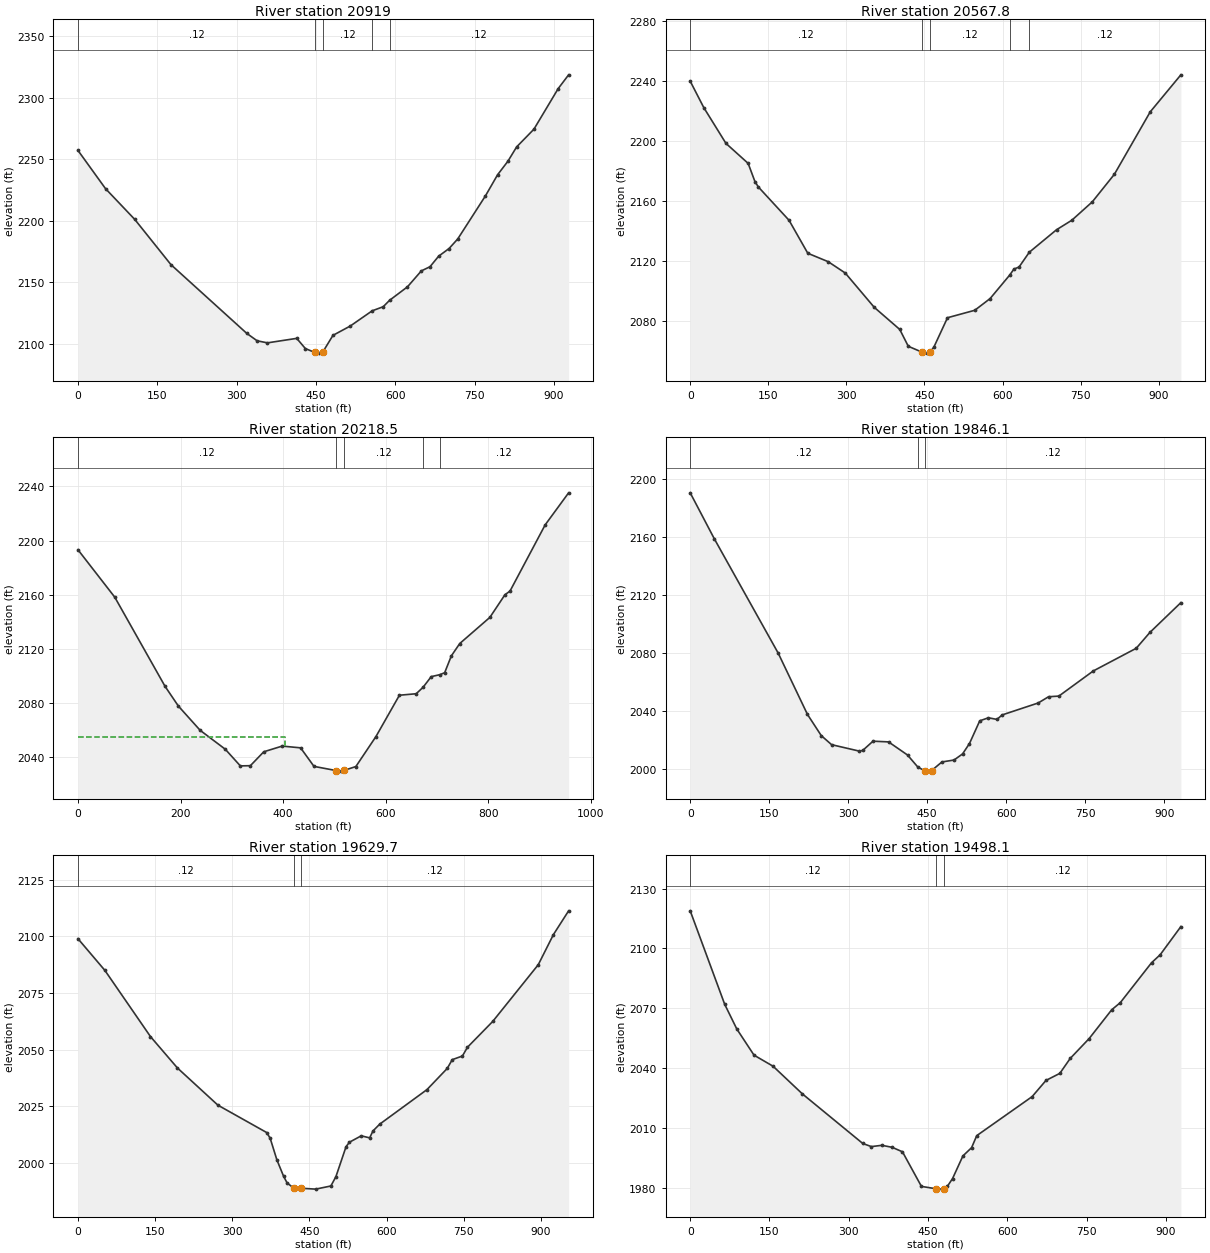
Type RM Length L Ch R = 1 ,20919   ,341.4,351.2,360
XS GIS Cut Line= 3
     2078400.127      209033.055     2077947.442      209024.124
     2077472.662      209010.256
#Sta/Elev= 30
       0 2257.28    52.1 2226.18   107.5 2201.09   175.9  2164.3   319.2 2108.41
   338.8 2102.36   358.3 2100.69   413.7 2104.34     430 2096.06  447.872092.873
     456 2092.33   462.6 2092.97   482.2  2106.8     515  2114.4  556.362126.761
   577.2 2130.09  589.292135.326   623.1 2146.28   649.3 2159.24   665.7 2162.64
   682.1 2171.24   701.7 2177.43   718.1 2185.21   770.5 2220.26   793.4  2237.4
   813.1 2248.53   829.5 2260.12   862.2 2274.54   908.1 2307.58   927.8 2318.77
#Mann= 5 ,-1 , 0
       0     .12       0  447.87    .045       0   462.6     .12       0
  556.36    .016       0  589.29     .12       0
Bank Sta=447.87,462.6
XS Rating Curve= 0 ,0
Exp/Cntr=0.3,0.1

Type RM Length L Ch R = 1 ,20567.8 ,342.3,349.2,335.3
XS GIS Cut Line= 3
     2078438.515      208891.081     2078011.158      208755.116
     2077583.622      208507.167
#Sta/Elev= 30
       0 2239.84    26.2 2222.17    68.7 2198.39   111.3 2185.08   124.4 2172.92
   130.9 2169.36   189.9 2147.15   225.9 2125.18   265.2 2119.55   297.9    2112
   353.5 2089.18   402.6 2074.41     419 2063.18   445.2 2059.31     455 2058.63
  460.632059.271   468.1 2062.59   494.3 2082.22   546.7 2087.18   576.1 2094.96
  613.742110.604   621.9 2114.62   631.8 2116.02  651.492125.871   703.8 2140.85
   733.2 2147.19   772.5 2159.43     815 2177.84   883.8  2219.4   942.7 2244.08
#Mann= 5 ,-1 , 0
       0     .12       0   445.2    .045       0  460.63     .12       0
  613.74    .016       0  651.49     .12       0
Bank Sta=445.2,460.63
XS Rating Curve= 0 ,0
Exp/Cntr=0.3,0.1

Type RM Length L Ch R = 1 ,20218.5 ,375,372.4,377.2
XS GIS Cut Line= 3
     2078522.848      208662.711     2078059.572      208451.756
     2077613.313      208420.254
#Sta/Elev= 30
       0 2193.21    71.8  2158.1   169.7  2092.2   195.8 2077.53   238.2 2059.62
   287.2 2045.62   316.5  2033.3   336.1 2033.45   362.2 2043.74   398.1 2047.96
     434 2046.65   460.1 2032.93   503.82029.807   512.3 2029.43   518.8 2029.99
   541.7 2032.82   580.9 2055.04   626.6 2085.58   659.3 2086.68  672.632091.437
   688.6 2099.33  705.642100.808   714.8 2102.24   727.8 2114.68   744.2 2123.83
   802.9 2143.17   832.3 2159.93   842.1  2162.6   910.7 2211.62   956.4 2235.31
#Mann= 5 ,-1 , 0
       0     .12       0   503.8    .045       0   518.8     .12       0
  672.63    .016       0  705.64     .12       0
#XS Ineff= 2 , 0
          403.62 2054.38
Permanent Ineff=
       F       F
Bank Sta=503.8,518.8
XS Rating Curve= 0 ,0
Exp/Cntr=0.3,0.1

Type RM Length L Ch R = 1 ,19846.1 ,221.6,216.4,208.4
XS GIS Cut Line= 3
      2078681.57      208409.162        2078280.      208201.847
     2077867.312      207957.116
#Sta/Elev= 30
       0 2190.75    45.8 2159.02     167  2080.2   222.7 2037.83   248.9 2023.22
   268.5 2016.99   320.9 2012.56   327.5    2013   347.1  2019.4   376.6 2018.91
   412.6 2009.87   432.3 2001.51   445.4 1998.98   448.6 1998.74   458.2 1999.08
     478 2005.08   500.9 2006.39   517.2 2010.63   530.3  2017.8   549.8 2033.45
   566.2 2035.54   582.5 2034.42   592.3 2037.51   660.8 2045.76   680.4 2050.06
     700 2050.51   765.3 2067.84   846.9 2083.49     873 2094.48   931.7 2114.99
#Mann= 3 ,-1 , 0
       0     .12       0   432.3    .045       0   445.4     .12       0
Bank Sta=445.4,458.2
XS Rating Curve= 0 ,0
Exp/Cntr=0.3,0.1

Type RM Length L Ch R = 1 ,19629.7 ,141,131.6,126.8
XS GIS Cut Line= 2
     2078812.223       208116.34     2077879.932      207914.517
#Sta/Elev= 30
       0 2099.03    52.4 2084.99     141 2055.72   193.4 2041.83   272.1 2025.38
   367.1 2013.25   373.7 2010.72   386.8 2001.15   399.9 1993.87   406.5 1991.02
   419.6 1988.64   432.7 1988.65   462.2 1988.24   491.7 1989.63   501.5 1993.76
   521.2 2007.02   527.8    2009   550.7 2011.82   567.1 2010.92   573.6 2013.99
   586.8 2017.01   678.5 2032.26   717.9 2041.63   727.7 2045.52   747.4 2047.12
   757.2 2050.99   806.4 2062.43   894.9 2087.52   924.4 2100.86   953.9 2111.35
#Mann= 3 ,-1 , 0
       0     .12       0   419.6    .045       0   432.7     .12       0
Bank Sta=419.6,432.7
XS Rating Curve= 0 ,0
Exp/Cntr=0.3,0.1

Type RM Length L Ch R = 1 ,19498.1 ,407.5,410,406.1
XS GIS Cut Line= 3
      2078804.16      207835.353     2078337.514      207915.951
     2077883.332      207887.325
#Sta/Elev= 30
       0 2118.84    65.3 2072.04    88.2 2059.69   120.8  2046.6   156.8 2041.07
   212.3 2027.22   326.6  2002.4   342.9 2000.84   362.5 2001.49   382.1  2000.5
   401.7 1998.24   437.6 1980.92   466.1 1979.71   476.8 1979.56   480.1 1979.75
   486.6 1980.93   496.5 1984.85   516.1 1996.18   532.5  2000.3   542.3 2006.33
   647.1 2025.86   673.3 2033.96   699.5 2037.49   719.1 2044.95   755.1 2054.94
   797.7 2069.32     814  2072.9     873 2092.83   889.4 2096.85   928.6 2110.96
#Mann= 3 ,-1 , 0
       0     .12       0   466.1    .045       0   480.1     .12       0
Bank Sta=466.1,480.1
XS Rating Curve= 0 ,0
Exp/Cntr=0.3,0.1

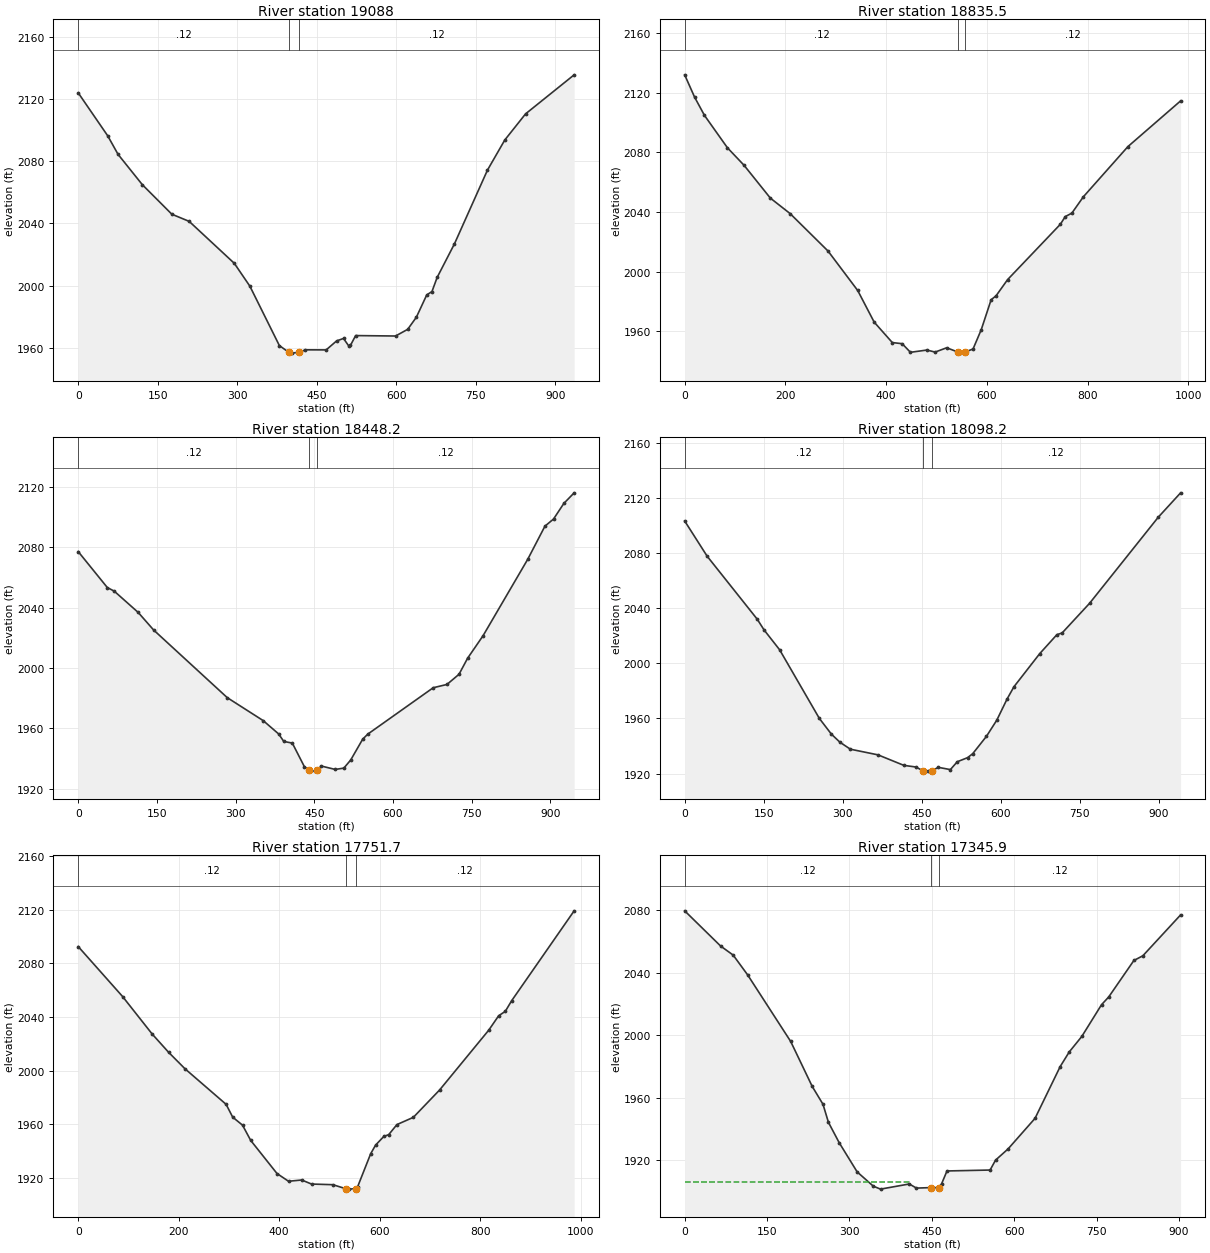
Type RM Length L Ch R = 1 ,19088   ,251.6,252.5,252.3
XS GIS Cut Line= 2
     2078794.645      207479.694     2077862.354      207556.083
#Sta/Elev= 30
       0 2124.19    55.6 2096.52    75.2 2084.52     121 2064.98   176.6 2045.97
   209.3 2041.36   294.4 2014.33   323.8 1999.58   379.4 1961.32  397.081957.004
   402.3 1956.45  416.811957.046   428.5 1958.58   467.7 1958.53   487.3 1964.31
   500.4 1965.91   510.2 1961.11   513.5 1961.48   523.3 1967.76   598.5 1967.48
   621.4 1971.77   637.8 1979.59   657.4 1993.99   667.2 1996.12     677 2005.24
   709.7 2026.92   771.9  2074.4   804.6 2093.81   843.8 2110.65   935.4  2135.8
#Mann= 3 ,-1 , 0
       0     .12       0  397.08    .045       0  416.81     .12       0
Bank Sta=397.08,416.81
XS Rating Curve= 0 ,0
Exp/Cntr=0.3,0.1

Type RM Length L Ch R = 1 ,18835.5 ,386.3,387.3,382.9
XS GIS Cut Line= 2
     2078806.798      207280.041     2077824.159      207342.541
#Sta/Elev= 30
       0 2132.12    19.6  2117.2    39.2 2104.94      85  2083.1   117.8 2071.44
   170.1 2049.37   209.4 2038.96   284.6 2013.85   343.5 1987.37   376.2 1966.14
   412.2 1952.41   431.8 1951.65   448.2 1945.87   480.9 1947.39   497.2 1946.02
   520.1 1948.91     543 1945.98   546.3 1945.32   556.1    1946   572.5 1948.09
   588.8 1961.07   608.4 1981.15   618.2  1983.8   641.2  1994.7   745.8 2031.79
   755.6 2036.97   768.7  2039.3   791.6 2050.29     880 2083.96   984.6 2114.64
#Mann= 3 ,-1 , 0
       0     .12       0     543    .045       0   556.1     .12       0
Bank Sta=543,556.1
XS Rating Curve= 0 ,0
Exp/Cntr=0.3,0.1

Type RM Length L Ch R = 1 ,18448.2 ,344,350,353.4
XS GIS Cut Line= 3
     2078776.263      206934.345     2078330.634      206973.957
      2077838.34      207050.097
#Sta/Elev= 30
       0 2077.07    55.5 2053.26    68.6  2050.9   114.3  2036.8   143.7 2025.18
   284.1 1980.37   352.7 1965.14   382.1 1956.33   391.9 1951.36   408.2 1950.26
   431.1  1934.7   439.9 1932.27   450.7  1931.7   454.9 1932.45   463.8 1935.04
     490 1932.82   506.4  1933.7   519.5 1939.07   542.4 1952.89   552.3 1956.26
   676.8 1986.92     703 1989.09     726 1995.83   742.3 2006.42   771.8 2021.34
     857 2071.97   889.8  2093.9   906.2 2098.63   925.9 2108.99   945.5 2115.98
#Mann= 3 ,-1 , 0
       0     .12       0   439.9    .045       0   454.9     .12       0
Bank Sta=439.9,454.9
XS Rating Curve= 0 ,0
Exp/Cntr=0.3,0.1

Type RM Length L Ch R = 1 ,18098.2 ,352.1,346.5,346.2
XS GIS Cut Line= 3
     2078745.326      206722.557     2078290.177      206666.424
     2077807.919      206681.935
#Sta/Elev= 30
       0 2103.27    42.6 2077.71   137.6 2032.02   150.7 2024.17   180.2 2009.78
   255.5 1960.01   278.4 1948.58   294.8 1942.64   314.5 1937.64   366.9 1933.53
     416  1925.9   438.9 1924.72     452 1921.98   461.9 1921.73   468.4 1921.92
   481.4 1924.47   504.2 1922.84   517.3 1928.55   536.8  1931.5   546.6 1934.39
   572.7 1947.01   592.3 1958.73   611.8 1974.08   624.9    1983   673.8 2007.02
   706.4 2020.79   716.2 2021.98   768.3  2043.5   898.7    2106   941.1 2123.69
#Mann= 3 ,-1 , 0
       0     .12       0     452    .045       0   468.4     .12       0
Bank Sta=452,468.4
XS Rating Curve= 0 ,0
Exp/Cntr=0.3,0.1

Type RM Length L Ch R = 1 ,17751.7 ,396.4,405.8,406.9
XS GIS Cut Line= 3
     2078747.287      206342.032     2078203.019      206416.378
       2077765.4      206417.845
#Sta/Elev= 30
       0 2092.51    88.3 2055.28   147.1 2027.37   179.8 2013.76   212.5 2001.44
   294.3 1974.96   307.4 1965.42     327 1959.43   343.3 1948.06   395.6  1923.4
   418.5 1917.64   444.7 1918.58   464.3 1915.57   506.8 1915.08     533 1912.02
   539.5 1911.78   552.6 1912.18   555.8 1913.34     582 1938.15   591.8  1944.6
   608.1 1951.01   617.9 1952.38   634.2 1959.86   666.9 1965.27   719.2 1985.67
   817.1  2030.3   836.7 2040.97   849.8  2044.2   862.8 2052.31   986.9 2119.13
#Mann= 3 ,-1 , 0
       0     .12       0     533    .045       0   552.6     .12       0
Bank Sta=533,552.6
XS Rating Curve= 0 ,0
Exp/Cntr=0.3,0.1

Type RM Length L Ch R = 1 ,17345.9 ,287.7,284.8,280.5
XS GIS Cut Line= 2
     2078749.506      206085.597     2077848.465      206030.041
#Sta/Elev= 30
       0 2079.71    65.4 2057.18    88.3 2051.36   114.5 2038.76     193 1996.08
   232.2 1967.28   251.8 1955.86   261.7 1944.31   281.3 1931.26     314 1912.58
   343.4 1903.45   356.5 1901.56   408.9 1904.86   421.9 1902.22   447.5 1902.53
   462.5 1902.51   467.7 1904.97   477.5 1913.19     556 1913.78   565.9 1920.12
   588.8 1927.33   637.8 1946.88   683.6 1980.03     700 1989.36   722.9 1999.29
   758.8  2019.6   771.9 2024.58   817.7 2047.92   834.1 2050.95   902.8 2077.11
#Mann= 3 ,-1 , 0
       0     .12       0   447.5    .045       0   462.5     .12       0
#XS Ineff= 2 , 0
          407.71 1906.39
Permanent Ineff=
       F       F
Bank Sta=447.5,462.5
XS Rating Curve= 0 ,0
Exp/Cntr=0.3,0.1