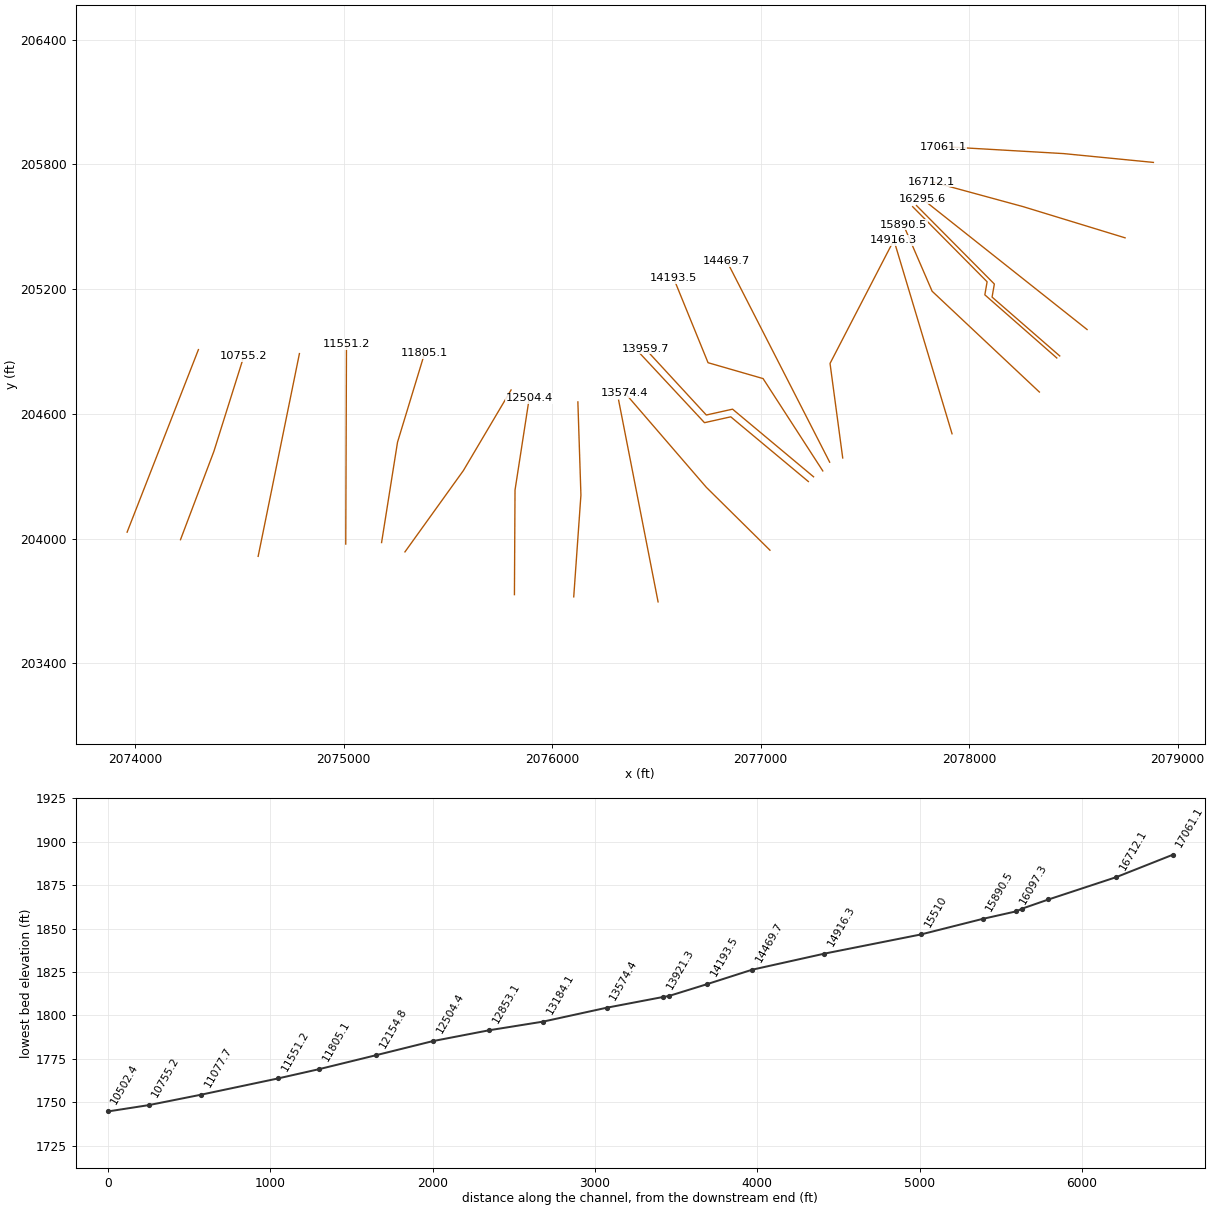
HEC-RAS study LAURELCK1.prj: LAURELCK1

--- LAURELCK1.g01 (geometry) --- (continued)

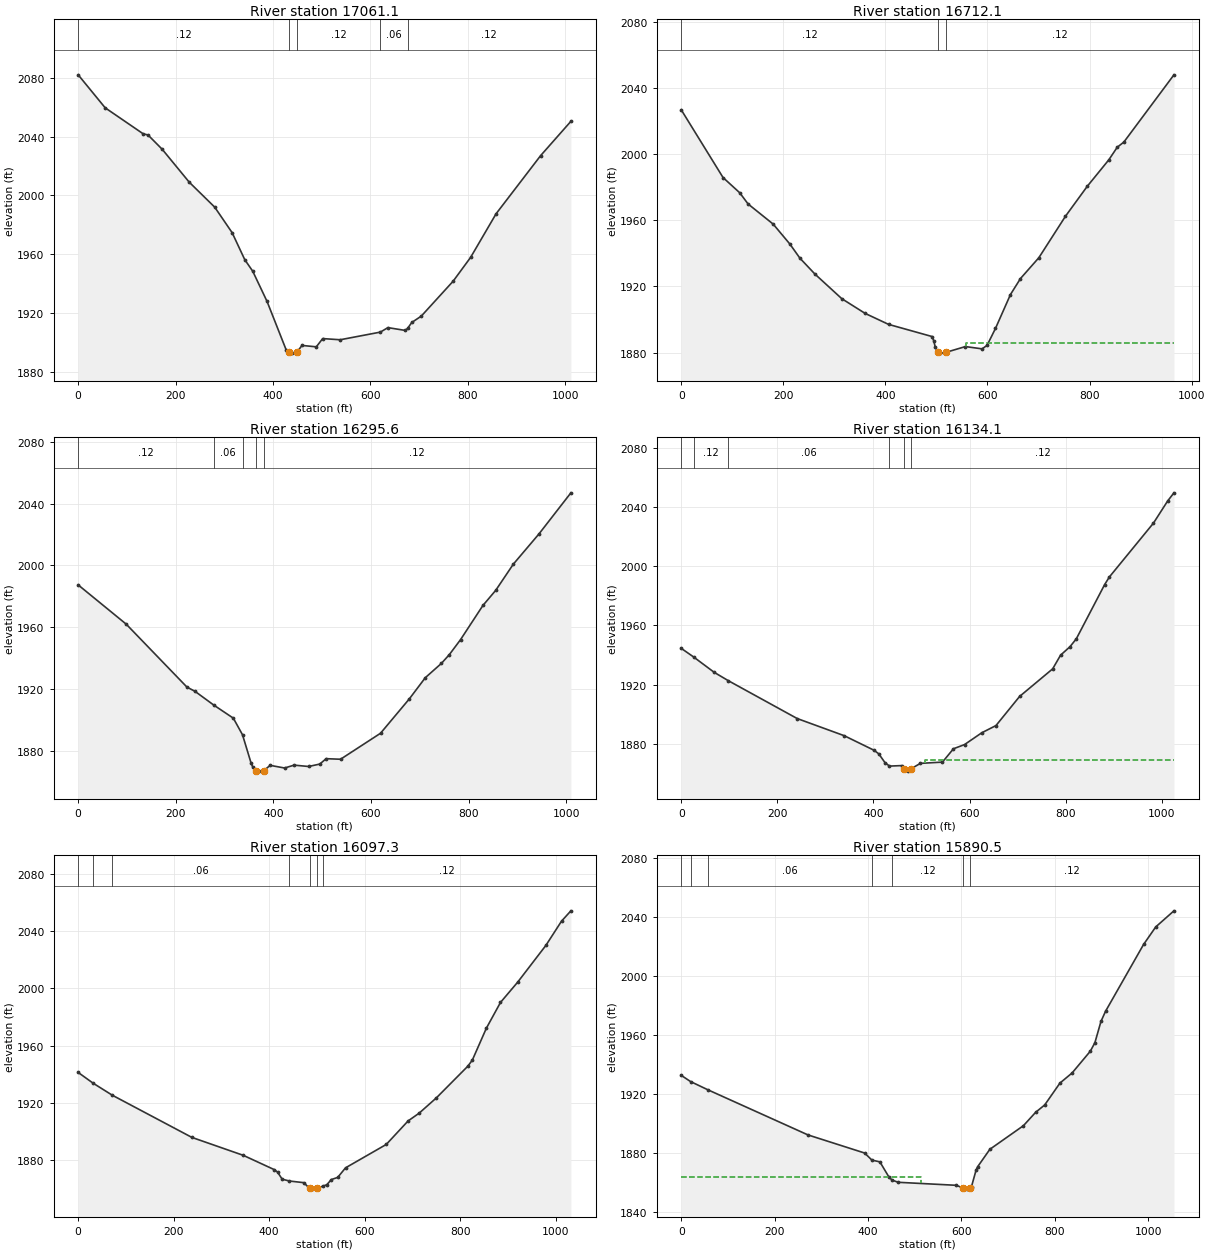
Type RM Length L Ch R = 1 ,17061.1 ,353.1,348.9,343.5
XS GIS Cut Line= 3
     2078883.597      205809.904     2078452.417      205852.371
     2077875.261      205885.863
#Sta/Elev= 30
       0 2082.05    55.4  2059.6   133.6 2041.86   143.3 2041.11   172.6 2031.32
     228 2008.95   280.2 1991.99     316  1974.6     342 1956.18   358.3 1948.35
   387.7 1927.78   426.8 1894.92   433.3 1893.35   439.8 1892.58   449.6 1893.46
   459.4 1897.82   488.8 1896.87   501.9 1902.48   537.8 1901.68  620.251906.885
   635.8 1909.94   671.7 1908.03  676.071909.375   684.8 1913.45   704.4 1917.81
   769.7 1941.56   805.6 1957.79   857.9 1987.49   949.3 2027.06  1011.4 2050.39
#Mann= 5 ,-1 , 0
       0     .12       0   433.3    .045       0   449.6     .12       0
  620.25     .06       0  676.07     .12       0
Bank Sta=433.3,449.6
XS Rating Curve= 0 ,0
Exp/Cntr=0.3,0.1

Type RM Length L Ch R = 1 ,16712.1 ,424.3,416.6,405.5
XS GIS Cut Line= 3
      2078747.82      205446.943     2078259.303      205596.862
     2077821.112      205716.612
#Sta/Elev= 30
       0 2026.77    81.9 1985.82   114.6 1976.61     131 1969.83   180.2 1957.65
   212.9 1945.59   232.6 1937.04     262 1927.44   314.5 1912.59   360.3 1903.68
   406.2 1897.04   491.4 1889.69   494.6 1887.24   497.9 1883.07   503.5 1880.11
   507.7 1879.66   518.5 1880.12   556.8 1883.63   589.4 1882.24   599.2 1884.35
   615.6 1894.55     645 1915.08   664.6 1924.74   700.6 1937.33   752.8 1962.42
   795.3 1980.44   837.8 1996.56   854.2 2004.13   867.2 2007.26   965.3 2047.91
#Mann= 3 ,-1 , 0
       0     .12       0   503.5    .045       0   518.5     .12       0
#XS Ineff= 2 , 0
                          557.12          1885.8
Permanent Ineff=
       F       F
Bank Sta=503.5,518.5
XS Rating Curve= 0 ,0
Exp/Cntr=0.3,0.1

Type RM Length L Ch R = 1 ,16295.6 ,185.1,161.4,138.1
XS GIS Cut Line= 2
     2078565.479      205005.736     2077775.548      205634.208
#Sta/Elev= 30
       0 1987.35    98.3 1961.98   222.9 1921.18   239.2  1918.5  277.731909.583
   317.9 1901.08  336.681890.334     354 1872.26   357.2 1869.77   363.8 1867.16
   370.4 1866.82   380.2 1867.11   393.3 1870.56   422.8 1868.84   442.4  1870.7
     472 1869.82   494.9 1871.38     508 1874.88   537.5 1874.51   619.4 1891.33
   678.4 1913.58   711.2 1927.31     744 1936.51   760.4 1942.24   783.3 1951.91
   829.2 1974.06   855.4 1983.84   891.4 2000.76   943.9 2020.31  1009.4 2046.95
#Mann= 5 ,-1 , 0
       0     .12       0  277.73     .06       0  336.68     .12       0
   363.8    .045       0   380.2     .12       0
Bank Sta=363.8,380.2
XS Rating Curve= 0 ,0
Exp/Cntr=0.3,0.1

Type RM Length L Ch R = 1 ,16134.1 ,36.9,36.8,34.9
XS GIS Cut Line= 4
     2078434.359      204878.537     2078109.923       205161.74
     2078120.774      205224.674      2077747.51      205602.278
#Sta/Elev= 30
       0 1944.56   25.551938.785    68.5 1928.37   98.031922.695   241.4 1897.11
   339.3 1885.51   401.3 1875.68   411.1 1873.27   424.1 1867.31  433.471864.975
   459.4 1865.32  463.891863.241   472.2 1861.57   478.6 1863.21   497.8 1866.82
   543.7 1867.67   566.6 1876.69   589.6  1879.5   625.6  1887.5   655.1 1892.37
   704.3 1912.06   773.1  1930.7   789.5 1939.93   809.2 1945.69   822.3    1951
   881.3 1987.67   891.1  1992.8   982.9 2029.22  1012.4 2044.16  1025.5 2049.67
#Mann= 6 ,-1 , 0
       0     .06       0   25.55     .12       0   98.03     .06       0
  433.47     .12       0  463.89    .045       0   478.6     .12       0
#XS Ineff= 2 , 0
                          508.33         1868.94
Permanent Ineff=
       F       F
Bank Sta=463.89,478.6
XS Rating Curve= 0 ,0
Exp/Cntr=0.3,0.1

Type RM Length L Ch R = 1 ,16097.3 ,183.8,206.9,228.8
XS GIS Cut Line= 4
     2078420.253      204868.771     2078075.201       205172.59
     2078086.052      205235.524     2077729.064      205596.853
#Sta/Elev= 30
       0 1941.35   31.241933.861   71.421925.473     238 1896.06   345.6 1883.56
   410.8 1873.54   417.4 1871.82   427.1 1866.92  442.151865.649   472.5 1864.49
  484.281860.487   488.5 1859.99  499.811860.568  512.93 1862.11   520.4 1863.05
   530.2 1866.69   543.3 1868.16   559.7 1874.83   644.9 1891.13   690.7 1907.54
   713.7 1912.92   749.7 1923.56   815.3 1945.56   825.1 1949.89   854.6 1972.24
   884.1 1990.16   920.1  2004.3   979.1 2029.91  1011.9 2046.84  1031.5 2054.03
#Mann= 7 ,-1 , 0
       0     .06       0   31.24     .12       0   71.42     .06       0
  442.15    .016       0  484.28    .045       0  499.81    .016       0
  512.93     .12       0
Bank Sta=484.28,499.81
XS Rating Curve= 0 ,0
Exp/Cntr=0.3,0.1

Type RM Length L Ch R = 1 ,15890.5 ,393,380.5,348.9
XS GIS Cut Line= 3
     2078336.703      204704.925      2077822.38      205189.951
     2077684.576      205510.047
#Sta/Elev= 30
       0 1932.68   19.921928.494    56.81922.944   271.6 1892.33   392.8 1880.09
  408.481875.286   425.5 1874.11   445.1 1863.73  451.751861.751   464.8 1860.27
   589.1 1858.23   604.2 1856.36     612 1855.64   619.2 1856.48   621.8 1857.39
   631.7 1868.66     635 1870.84   661.1 1882.61     733  1898.6   759.1 1907.64
   778.6 1912.65   811.2 1927.44   837.2 1934.28   876.3 1949.04   886.1 1954.81
   899.1  1969.2   908.9 1976.08   990.3 2021.28  1016.4 2033.18  1055.4 2044.08
#Mann= 7 ,-1 , 0
       0     .06       0   19.92     .12       0    56.8     .06       0
  408.48    .016       0  451.75     .12       0   604.2    .045       0
   619.2     .12       0
#XS Ineff= 2 , 0
          513.13 1863.61
Permanent Ineff=
       F       F
Bank Sta=604.2,619.2
XS Rating Curve= 0 ,0
Exp/Cntr=0.3,0.1

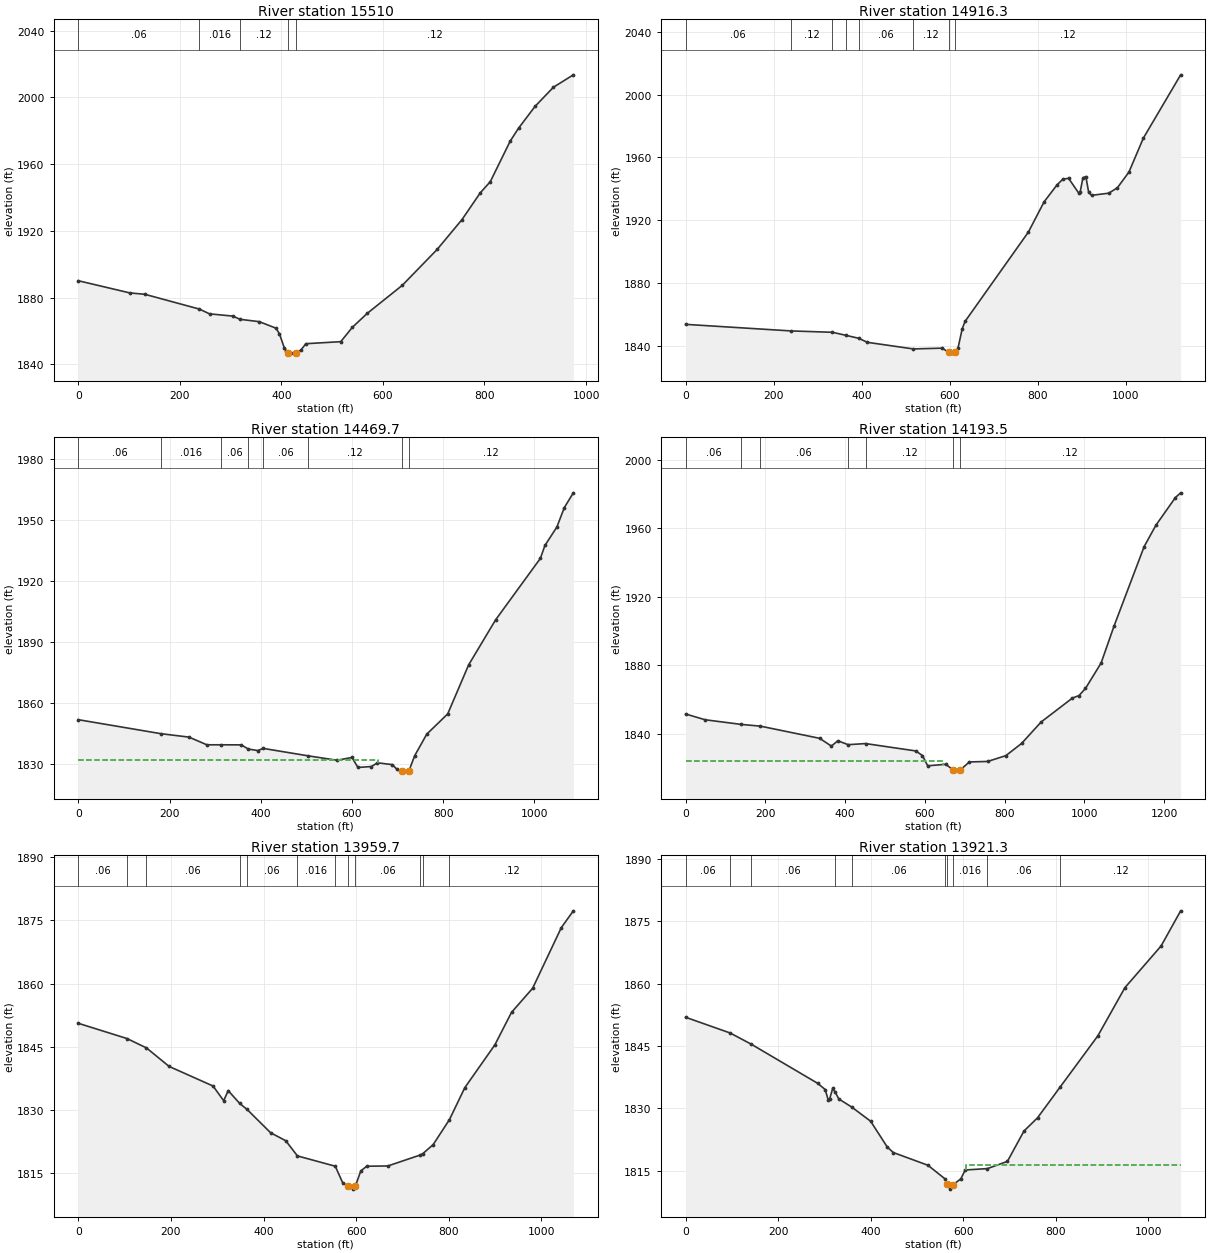
Type RM Length L Ch R = 1 ,15510   ,610.3,593.7,574.8
XS GIS Cut Line= 2
     2077917.909      204503.999     2077638.395      205438.027
#Sta/Elev= 30
       0 1890.08   101.4 1882.78   130.9 1881.96  238.46 1873.08   258.5 1870.22
   304.3 1868.88  318.491866.954   356.6 1865.52   389.3 1861.63   395.9 1858.43
   405.7 1849.87     409 1848.06     4141846.954     422 1846.67  429.741847.001
   438.4  1848.5   448.2 1852.32   516.9 1853.54   539.8 1862.15   569.3 1870.57
     638 1887.29   706.7 1908.82   755.8 1926.78   791.7 1942.78   811.4 1949.46
   850.6 1973.76     867  1981.5   899.7 1994.66   935.7 2006.08     975 2013.54
#Mann= 5 ,-1 , 0
       0     .06       0  238.46    .016       0  318.49     .12       0
     414    .045       0  429.74     .12       0
Bank Sta=414,429.74
XS Rating Curve= 0 ,0
Exp/Cntr=0.3,0.1

Type RM Length L Ch R = 1 ,14916.3 ,422.3,446.6,467.5
XS GIS Cut Line= 3
     2077393.604       204387.68      2077332.84      204842.541
     2077638.395      205434.555
#Sta/Elev= 30
       0 1853.92  239.381849.743   333.81848.877   363.61846.985   393.41845.064
     413  1842.5  517.531838.297     583 1838.79     598 1836.16   605.9 1835.63
     613 1836.09   618.9 1838.59   628.7 1851.19   635.2 1855.84     779 1912.58
   814.9 1931.87   844.3 1942.63   857.3  1946.2   870.4 1946.74   893.2 1937.45
   896.5 1937.83     903 1947.08   909.6 1947.86   916.1 1937.77   922.6 1935.93
   961.8 1937.29   981.4 1940.78  1007.6 1950.73  1040.2 1972.23  1125.1 2012.52
#Mann= 8 ,-1 , 0
       0     .06       0  239.38     .12       0   333.8    .016       0
   363.6     .08       0   393.4     .06       0  517.53     .12       0
     598    .045       0     613     .12       0
Bank Sta=598,613
XS Rating Curve= 0 ,0
Exp/Cntr=0.3,0.1

Type RM Length L Ch R = 1 ,14469.7 ,256.6,276.2,293.7
XS GIS Cut Line= 2
     2077331.021      204367.423     2076837.965      205334.437
#Sta/Elev= 30
       0 1851.66  181.551844.755   242.7 1843.08     282 1839.29  311.961839.299
   357.4 1839.26  372.88 1837.19   393.5 1836.46  405.631837.518  504.091833.854
   567.3 1831.69   600.1 1833.06   613.2 1828.14   642.8  1828.6   655.9 1830.42
   688.7 1829.53   698.5 1827.27  710.021826.549   718.2 1826.33  725.131826.567
   737.8    1834   764.1 1844.54     810  1854.5   855.9 1878.64   914.9 1900.78
  1013.3 1931.13  1023.2 1937.46  1049.4 1946.54  1065.8 1956.14  1085.5 1963.38
#Mann= 8 ,-1 , 0
       0     .06       0  181.55    .016       0  311.96     .06       0
  372.88    .016       0  405.63     .06       0  504.09     .12       0
  710.02    .045       0  725.13     .12       0
#XS Ineff= 2 , 0
          658.23 1831.73
Permanent Ineff=
       F       F
Bank Sta=710.02,725.13
XS Rating Curve= 0 ,0
Exp/Cntr=0.3,0.1

Type RM Length L Ch R = 1 ,14193.5 ,198.9,233.8,245.7
XS GIS Cut Line= 4
     2077298.118       204325.18     2077011.659      204769.624
      2076747.77      204846.013      2076582.84      205252.263
#Sta/Elev= 30
       0 1851.43      49 1848.05  139.711845.337  187.761844.316   336.2 1837.21
   365.6 1832.68   381.9 1835.78  407.73  1833.5  451.331834.147   577.8 1829.83
   594.2  1827.1   607.2 1821.18     653 1822.02  671.531818.617   675.9 1818.05
     688 1818.56   711.9 1823.42   757.7  1823.7   803.5 1827.11   842.8 1834.21
   891.8 1846.74   970.4 1860.74   986.7 1862.16  1003.1 1866.33  1042.3 1881.19
  1075.1    1903  1150.3 1949.21  1179.8 1961.69  1228.8 1977.88  1241.9 1980.61
#Mann= 7 ,-1 , 0
       0     .06       0  139.71    .016       0  187.76     .06       0
  407.73    .016       0  451.33     .12       0  671.53    .045       0
     688     .12       0
#XS Ineff= 2 , 0
          645.83 1823.79
Permanent Ineff=
       F       F
Bank Sta=671.53,688
XS Rating Curve= 0 ,0
Exp/Cntr=0.3,0.1

Type RM Length L Ch R = 1 ,13959.7 ,59.6,38.4,39
XS GIS Cut Line= 4
     2077253.803      204296.939     2076865.348       204622.46
      2076739.48      204594.248     2076446.512      204913.259
#Sta/Elev= 30
       0 1850.57  105.161846.956  147.121844.739   196.2 1840.34     291  1835.7
   313.9 1832.22   323.7 1834.61  348.271831.599  364.581830.137   415.3 1824.62
     448 1822.73  473.131819.136  554.86 1816.69   571.3 1812.67  582.651811.957
   593.9 1811.26  598.161811.931     610 1815.58   622.9 1816.69   668.4 1816.75
  738.631819.357  743.641819.656   766.1 1821.79  801.461827.747   834.5  1835.3
   899.6 1845.48   935.4 1853.16     981 1858.87  1042.9 1873.24  1068.9 1877.23
#Mann= 12 ,-1 , 0
       0     .06       0  105.16    .016       0  147.12     .06       0
  348.27     .12       0  364.58     .06       0  473.13    .016       0
  554.86     .08       0  582.65    .045       0  598.16     .06       0
  738.63     .12       0  743.64     .06       0  801.46     .12       0
Bank Sta=582.65,598.16
XS Rating Curve= 0 ,0
Exp/Cntr=0.3,0.1

Type RM Length L Ch R = 1 ,13921.3 ,369.4,346.8,320
XS GIS Cut Line= 4
     2077228.847      204274.153     2076856.668      204585.568
       2076730.8      204557.356      2076420.47      204891.557
#Sta/Elev= 30
       0 1851.91    96.11848.143  141.681845.459   285.3 1836.06   301.7 1834.56
   308.2  1832.1   311.5 1832.34     318 1834.83  323.511833.921   331.2 1832.29
  358.731830.373     400 1826.94   436.1 1820.72   449.2 1819.41     524 1816.36
  561.041813.073  565.26 1811.75   572.4 1810.63   578.8 1811.73   594.9  1813.1
   604.6 1815.23  652.391815.559   695.7 1817.29   731.5 1824.58   760.9 1827.77
  809.611835.136   891.2 1847.44   949.8 1859.03    1028 1869.04  1070.3 1877.48
#Mann= 10 ,-1 , 0
       0     .06       0    96.1    .016       0  141.68     .06       0
  323.51     .12       0  358.73     .06       0  561.04    .016       0
  565.26    .045       0   578.8    .016       0  652.39     .06       0
  809.61     .12       0
#XS Ineff= 2 , 0
                          606.48         1816.42
Permanent Ineff=
       F       F
Bank Sta=565.26,578.8
XS Rating Curve= 0 ,0
Exp/Cntr=0.3,0.1

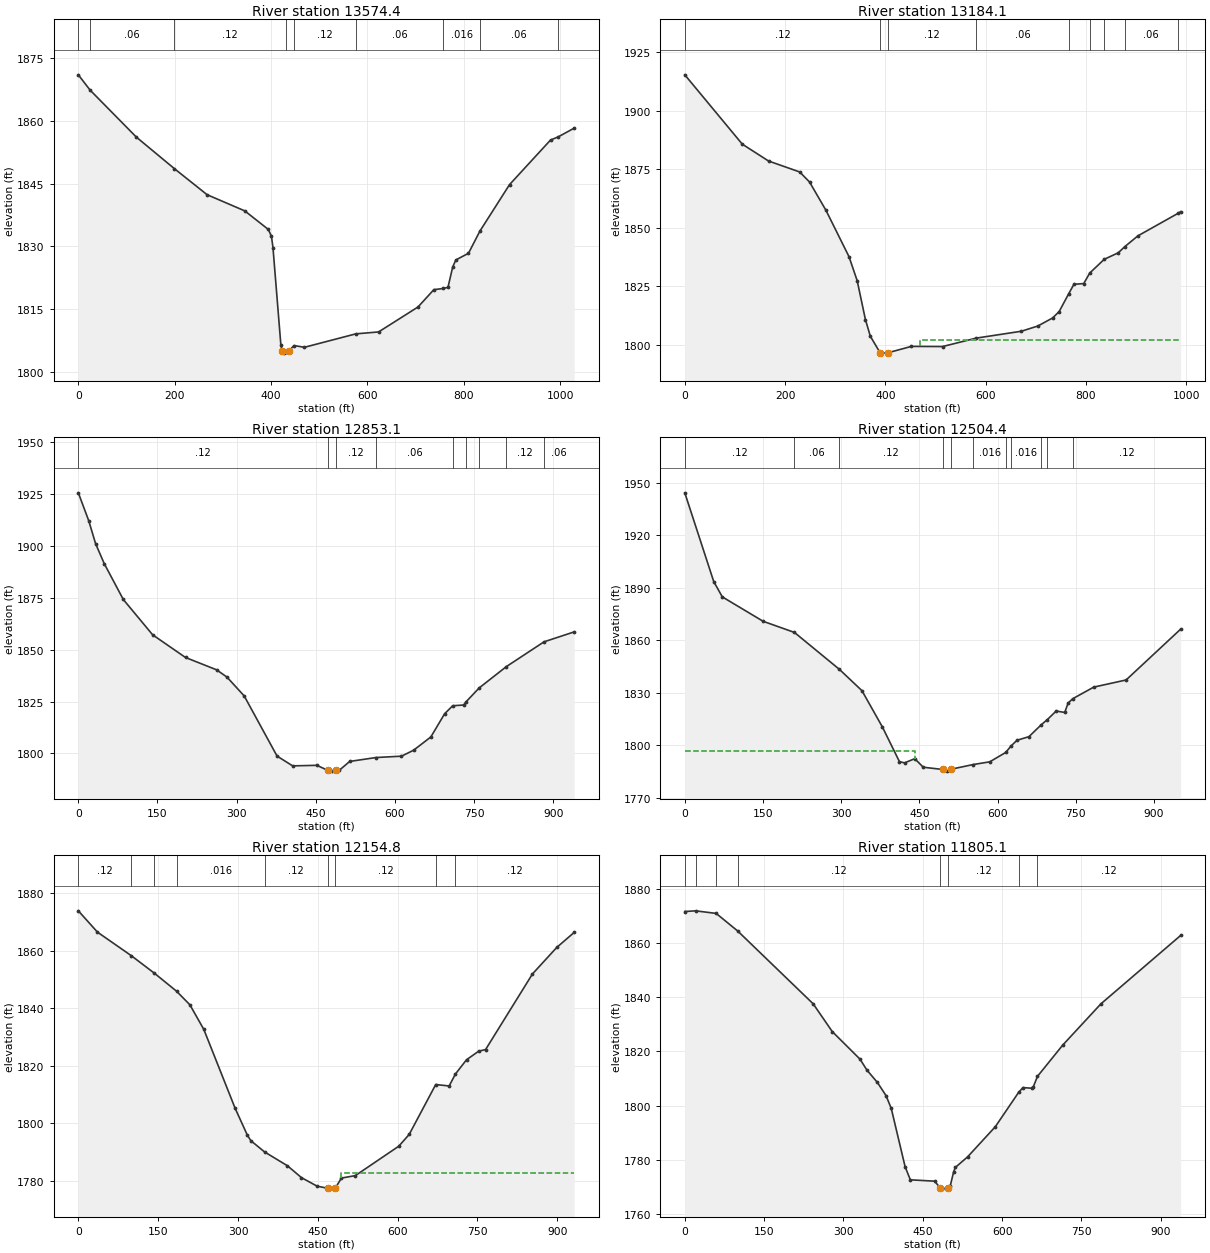
Type RM Length L Ch R = 1 ,13574.4 ,403.4,390.4,377.4
XS GIS Cut Line= 3
     2077044.666      203943.754     2076739.289      204246.593
      2076348.92      204700.999
#Sta/Elev= 30
       0 1871.04   24.391867.387   120.6 1856.12  199.541848.574   267.2 1842.36
   345.4 1838.49   394.2 1834.06   400.8 1832.42     404 1829.68   420.3  1806.5
  422.85    1805   426.8 1804.45   430.1 1804.62   436.6 1804.98  447.78 1806.26
   469.4 1805.85  576.031809.063   623.2 1809.52   705.1  1815.5   737.8 1819.63
  757.651819.927   767.2  1820.2   777.1 1825.09   783.6 1826.75   809.8 1828.34
  833.361833.626   894.9 1844.76     980 1855.43  996.141856.204  1029.1 1858.28
#Mann= 9 ,-1 , 0
       0     .12       0   24.39     .06       0  199.54     .12       0
   430.1    .045       0  447.78     .12       0  576.03     .06       0
  757.65    .016       0  833.36     .06       0  996.14     .12       0
Bank Sta=422.85,436.6
XS Rating Curve= 0 ,0
Exp/Cntr=0.3,0.1

Type RM Length L Ch R = 1 ,13184.1 ,335.6,331,325.2
XS GIS Cut Line= 2
     2076508.187      203694.972     2076318.951      204665.458
#Sta/Elev= 30
       0 1915.24   114.6 1885.66     167 1878.46   229.2 1873.78   248.8 1869.49
   281.6 1857.39   327.4 1837.67   343.8 1827.36   360.2 1810.81     370 1803.68
   389.6 1796.59   402.7 1796.47  404.27 1796.58   451.8 1799.34     514 1799.28
  581.241802.877   671.2 1805.81   703.9 1808.03   733.4 1811.46   746.5 1814.19
  765.82  1821.9     776 1825.84   795.6 1826.16  807.571830.651  836.471836.513
   864.4 1839.28  876.911841.808   903.6 1846.52  983.151856.067   988.8 1856.82
#Mann= 9 ,-1 , 0
       0     .12       0   389.6    .045       0  404.27     .12       0
  581.24     .06       0  765.82    .016       0  807.57     .06       0
  836.47    .016       0  876.91     .06       0  983.15     .12       0
#XS Ineff= 2 , 0
                          469.06         1802.17
Permanent Ineff=
       F       F
Bank Sta=389.6,404.27
XS Rating Curve= 0 ,0
Exp/Cntr=0.3,0.1

Type RM Length L Ch R = 1 ,12853.1 ,346.4,348.6,344.9
XS GIS Cut Line= 3
     2076103.632      203719.235     2076138.152       204209.29
     2076123.484      204657.378
#Sta/Elev= 30
       0 1925.37    19.6 1912.03    32.8 1900.85    49.1 1891.32    85.2 1874.07
   140.8 1857.08   203.1 1846.17     262 1840.24   281.7 1836.73   314.4 1827.65
   376.6 1798.75   406.1 1794.04     452  1794.3  472.811791.881   481.4 1791.51
     488 1791.88   494.5 1791.91   514.2 1796.17  564.191798.053   612.4  1798.7
   635.3 1801.56     668 1807.94   694.2 1819.13  709.441822.954   730.2 1823.31
  734.731824.841  759.631831.536  811.171841.794   882.51853.704   939.6 1858.48
#Mann= 9 ,-1 , 0
       0     .12       0  472.81    .045       0     488     .12       0
  564.19     .06       0  709.44    .016       0  734.73     .12       0
  759.63     .06       0  811.17     .12       0   882.5     .06       0
Bank Sta=472.81,488
XS Rating Curve= 0 ,0
Exp/Cntr=0.3,0.1

Type RM Length L Ch R = 1 ,12504.4 ,361.9,349.6,338.9
XS GIS Cut Line= 3
     2075819.263      203729.891     2075822.074      204232.933
     2075890.238      204675.538
#Sta/Elev= 30
       0 1944.25    55.5 1893.54    71.9  1884.8   150.3 1870.83  210.251864.486
  296.241843.444   339.7 1831.22   378.9 1810.49   411.6 1790.67   421.4 1789.94
     441 1792.34   457.3 1787.46  494.611786.182     503 1785.23   509.6 1786.26
  553.211789.001   584.8 1790.54  615.661795.923  625.191799.452   637.1 1802.87
     660 1804.92  683.541811.699  695.431814.713   712.2 1819.57   728.6 1818.76
   735.1 1824.08  743.741826.559   784.2 1833.23   846.3 1837.31   950.9 1866.34
#Mann= 11 ,-1 , 0
       0     .12       0  210.25     .06       0  296.24     .12       0
  494.61    .045       0   509.6     .12       0  553.21    .016       0
  615.66     .12       0  625.19    .016       0  683.54     .12       0
  695.43    .016       0  743.74     .12       0
#XS Ineff= 2 , 0
          442.06 1796.65
Permanent Ineff=
       F       F
Bank Sta=494.61,509.6
XS Rating Curve= 0 ,0
Exp/Cntr=0.3,0.1

Type RM Length L Ch R = 1 ,12154.8 ,338.4,349.7,355.1
XS GIS Cut Line= 3
     2075294.242      203935.566      2075574.46      204326.971
     2075803.228      204714.885
#Sta/Elev= 30
       0 1873.94      36 1866.52   99.691858.318  143.111852.206  184.491845.985
   209.6 1841.25   235.8 1832.68   294.7 1805.21   317.6 1795.89   324.2 1793.96
  349.921790.061     393 1785.23   419.2 1781.12   448.6 1778.15   468.3 1777.42
   481.4 1777.11  482.731777.434   494.4 1780.96   520.5 1781.81   602.1 1792.04
   621.7 1796.14  671.591813.502   696.8    1813   708.61817.157   729.4 1822.12
   752.2 1825.09   765.3 1825.68   853.4 1851.99   899.1 1861.22   931.7 1866.42
#Mann= 9 ,-1 , 0
       0     .12       0   99.69    .016       0  143.11     .12       0
  184.49    .016       0  349.92     .12       0   468.3    .045       0
  482.73     .12       0  671.59    .016       0   708.6     .12       0
#XS Ineff= 2 , 0
                          494.16         1782.86
Permanent Ineff=
       F       F
Bank Sta=468.3,482.73
XS Rating Curve= 0 ,0
Exp/Cntr=0.3,0.1

Type RM Length L Ch R = 1 ,11805.1 ,249.1,253.9,259.8
XS GIS Cut Line= 3
     2075182.133      203980.444     2075258.529      204463.227
     2075388.817       204892.73
#Sta/Elev= 30
       0 1871.71   20.391871.969   59.321871.012   99.911864.534   242.8 1837.59
   278.8 1827.35   331.3 1817.15   344.4  1813.1   364.1 1808.56   380.5 1803.68
   390.4 1798.94   416.6 1777.38   426.5 1772.54   472.4 1772.04   483.11769.551
   485.5  1769.1   498.6  1769.6   501.9 1770.25   508.4  1775.5   511.7 1777.14
   534.7 1781.01   587.1 1792.15  631.361804.888   639.5 1806.63   655.9  1806.4
   659.2 1806.99  666.891810.779   714.8 1822.37   786.9 1837.59   937.6 1862.86
#Mann= 8 ,-1 , 0
       0     .06       0   20.39    .016       0   59.32     .06       0
   99.91     .12       0   483.1    .045       0   498.6     .12       0
  631.36    .016       0  666.89     .12       0
Bank Sta=483.1,498.6
XS Rating Curve= 0 ,0
Exp/Cntr=0.3,0.1

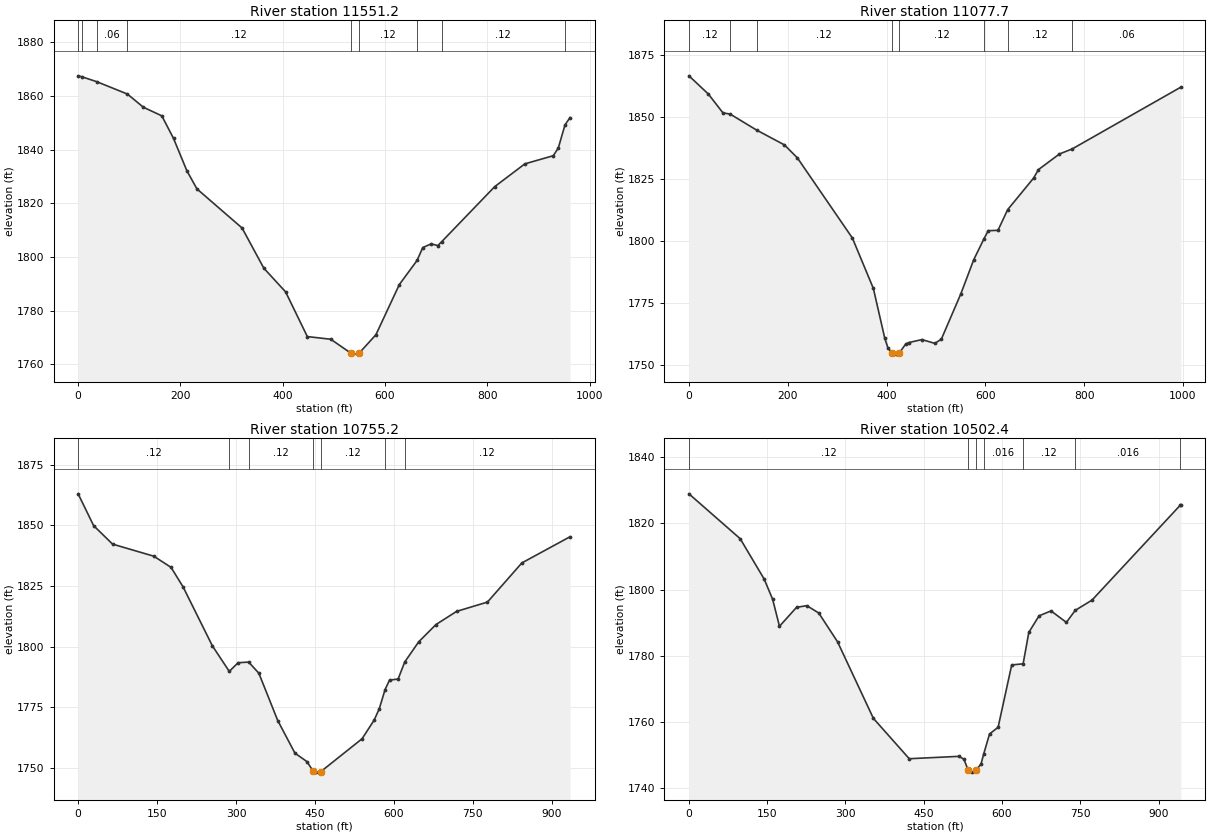
Type RM Length L Ch R = 1 ,11551.2 ,477.9,473.5,465.1
XS GIS Cut Line= 2
     2075010.357      203973.184     2075013.829      204934.989
#Sta/Elev= 30
       0 1867.52    7.011867.176    36.3 1865.34   96.321860.724   127.6  1855.8
   163.6  1852.6   186.5 1844.18   212.6 1832.13   232.3 1825.35   320.6 1810.76
   363.1 1795.78   405.7 1786.94   448.2 1770.27     494 1769.28   533.2 1764.11
   546.3 1763.73   549.6 1764.12   582.3 1770.97   628.1 1789.69  662.69 1798.65
   673.9 1803.48   690.3 1804.84   703.4 1804.21  710.651805.614   814.6  1826.2
   873.5 1834.69   929.1 1837.73   938.9 1840.59     952 1849.22   961.8 1851.94
#Mann= 9 ,-1 , 0
       0     .12       0    7.01    .016       0    36.3     .06       0
   96.32     .12       0   533.2    .045       0   549.6     .12       0
  662.69    .016       0  710.65     .12       0     952     .06       0
Bank Sta=533.2,549.6
XS Rating Curve= 0 ,0
Exp/Cntr=0.3,0.1

Type RM Length L Ch R = 1 ,11077.7 ,325,322.5,319.4
XS GIS Cut Line= 2
     2074590.218      203914.156     2074788.135       204889.85
#Sta/Elev= 30
       0 1866.58    39.3 1859.23    68.8 1851.65   83.49 1851.15  136.751844.725
   193.2 1838.74   219.4 1833.52   330.8 1801.18   373.3 1780.85   396.3 1760.81
   402.8 1756.88  410.671754.847   419.2 1754.37   425.7  1754.8   438.8 1758.47
   445.4 1759.05   471.6 1760.23   497.8  1758.7   510.9 1760.42   550.2 1778.61
   576.4 1792.42  597.191800.889   605.8 1804.14   625.5 1804.28   645.11812.618
   697.6 1825.35   707.4 1828.76     750 1835.08  775.921837.125   995.6 1862.01
#Mann= 8 ,-1 , 0
       0     .12       0   83.49    .016       0  136.75     .12       0
  410.67    .045       0   425.7     .12       0  597.19    .016       0
   645.1     .12       0  775.92     .06       0
Bank Sta=410.67,425.7
XS Rating Curve= 0 ,0
Exp/Cntr=0.3,0.1

Type RM Length L Ch R = 1 ,10755.2 ,253.5,252.8,250.3
XS GIS Cut Line= 3
      2074217.82      203994.311     2074378.046      204419.566
     2074521.694       204877.62
#Sta/Elev= 30
       0 1862.93    29.4 1849.84    65.4 1842.23   143.8 1837.25   176.5 1832.66
   199.4 1824.61     255 1800.37  287.111789.842     304  1793.4     3241793.656
   343.3 1789.09   379.2 1769.61   411.9 1756.18   434.8 1752.68   446.9 1748.62
   451.2 1748.36     461 1748.56   539.4 1762.09   562.2  1769.7     572 1774.37
  583.211782.373   591.6 1786.25   607.9 1786.68  620.491793.692   647.1 1802.02
   679.8 1809.11     719 1814.53   777.7 1818.37     843 1834.48   934.5 1845.25
#Mann= 7 ,-1 , 0
       0     .12       0  287.11    .016       0     324     .12       0
   446.9    .045       0     461     .12       0  583.21    .016       0
  620.49     .12       0
Bank Sta=446.9,461
XS Rating Curve= 0 ,0
Exp/Cntr=0.3,0.1

Type RM Length L Ch R = 1 ,10502.4 ,447.2,447.2,448.3
XS GIS Cut Line= 2
     2073961.746      204030.475      2074303.76      204908.947
#Sta/Elev= 30
       0 1828.98    98.2 1815.39     144 1803.21   160.4 1797.04   173.5 1788.86
   206.2  1794.6   225.9 1795.11   248.8 1792.88   284.8 1784.16   353.5 1760.97
   422.2 1748.75   517.2 1749.47     527 1748.61  535.111745.284   543.4 1744.69
   549.9 1745.29   559.7 1747.09  564.771750.112   576.1 1756.25   592.5 1758.27
   618.6 1777.16  640.461777.492   651.4 1787.03     671 1792.03   693.9 1793.52
   723.4 1790.04  740.271793.676   772.5 1796.79  942.051825.605   942.7 1825.68
#Mann= 7 ,-1 , 0
       0     .12       0  535.11    .045       0   549.9     .12       0
  564.77    .016       0  640.46     .12       0  740.27    .016       0
  942.05     .12       0
Bank Sta=535.11,549.9
XS Rating Curve= 0 ,0
Exp/Cntr=0.3,0.1