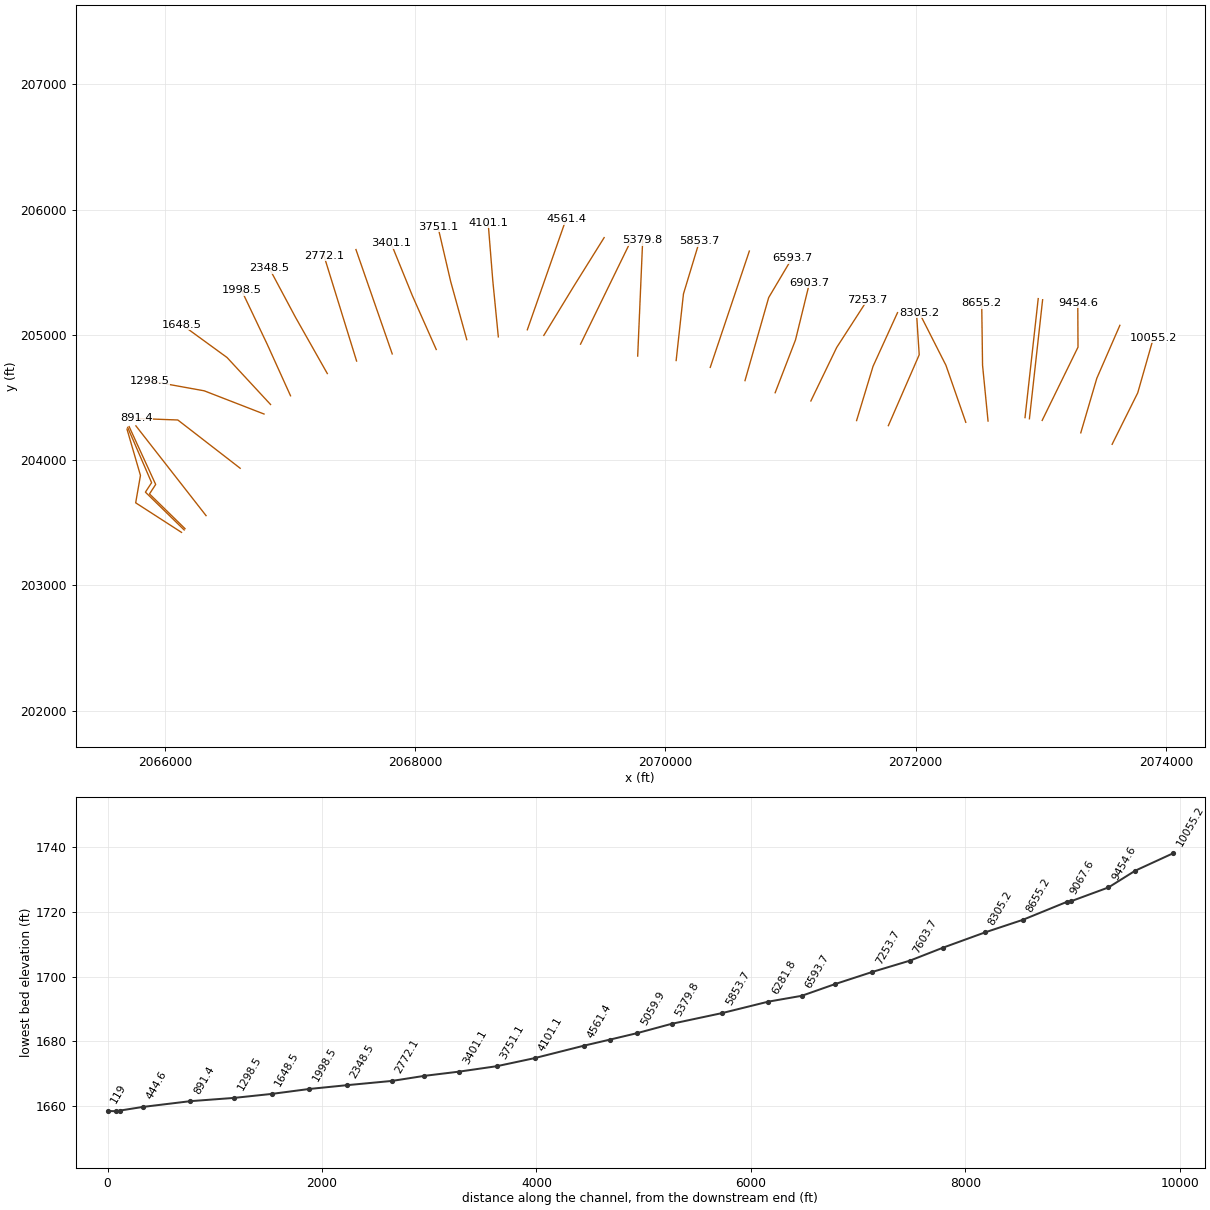
HEC-RAS study LAURELCK1.prj: LAURELCK1

--- LAURELCK1.g01 (geometry) --- (continued)

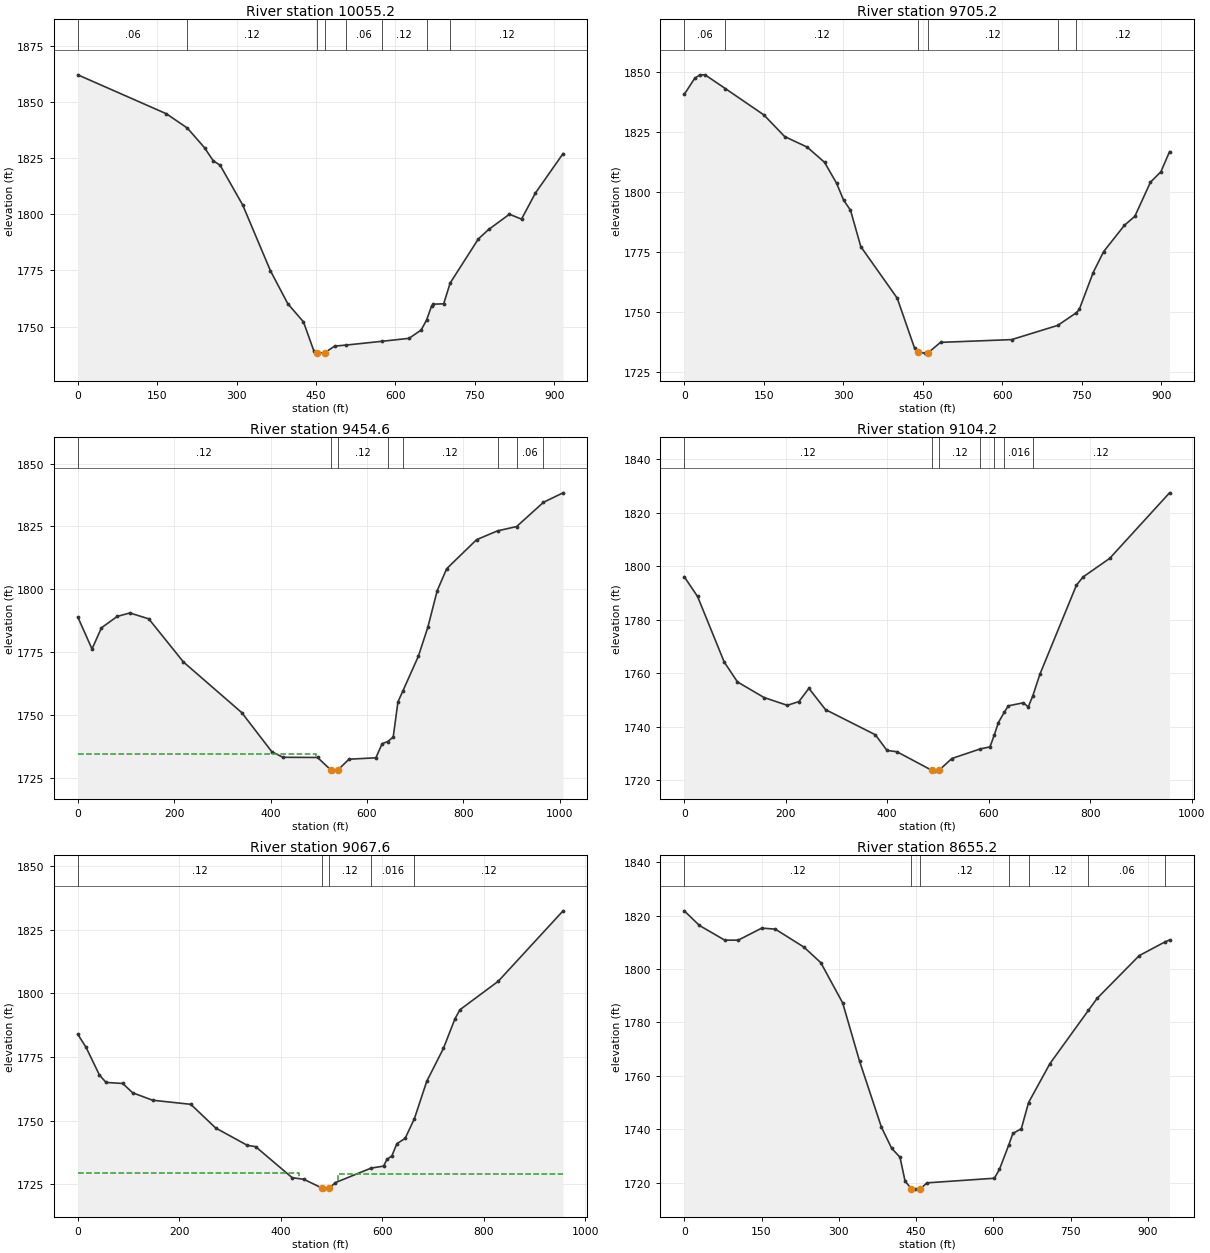
Type RM Length L Ch R = 1 ,10055.2 ,345.7,350,346.4
XS GIS Cut Line= 3
     2073571.257      204126.234     2073776.007      204537.208
     2073901.636      204977.371
#Sta/Elev= 30
       0 1862.21   167.3 1844.86   207.11838.456   239.4 1829.72   255.8 1823.93
   268.9 1821.91   311.6 1804.16     364 1774.85   396.8 1760.16   426.4 1752.07
     446 1739.14   451.7 1738.19   452.6 1738.14   466.7 1738.33   485.3 1741.27
  507.081741.736  574.93 1743.42   625.9 1744.74   648.8 1748.45  659.061752.931
   668.4 1759.11   671.7 1759.96   691.3 1760.13  703.591769.406   756.7 1789.01
   776.3 1793.27   815.5 1800.05   838.4 1797.89   864.6 1809.49   916.9  1827.1
#Mann= 8 ,-1 , 0
       0     .06       0   207.1     .12       0   451.7    .045       0
   466.7     .12       0  507.08     .06       0  574.93     .12       0
  659.06    .016       0  703.59     .12       0
Bank Sta=451.7,466.7
XS Rating Curve= 0 ,0
Exp/Cntr=0.3,0.1

Type RM Length L Ch R = 1 ,9705.2  ,253.8,250.6,249.2
XS GIS Cut Line= 3
     2073320.802      204217.871     2073448.863       204653.29
     2073633.172      205076.342
#Sta/Elev= 30
       0 1840.51    19.6 1847.16    29.4 1848.64    39.2 1848.64   77.751842.879
   150.2 1831.95   189.4 1822.94   231.8 1818.56   264.5 1812.24   287.3 1803.51
   300.4 1796.53   313.5 1792.31     333 1777.12   401.6  1755.7   434.3 1734.94
   440.8 1733.12   453.9  1732.8   460.4 1733.04   483.3 1737.28   617.5 1738.43
  704.411744.345  739.431749.593   745.1 1751.01   771.3 1766.36     791 1775.06
   830.2 1786.01   849.9 1789.77   879.3 1803.96     899 1808.29   915.3 1816.67
#Mann= 6 ,-1 , 0
       0     .06       0   77.75     .12       0   440.8    .045       0
   460.4     .12       0  704.41    .016       0  739.43     .12       0
Bank Sta=440.8,460.4
XS Rating Curve= 0 ,0
Exp/Cntr=0.3,0.1

Type RM Length L Ch R = 1 ,9454.6  ,337.5,350.4,357.7
XS GIS Cut Line= 3
     2073012.093      204316.934     2073298.552      204902.003
     2073296.816      205257.906
#Sta/Elev= 30
       0 1788.94    29.5 1776.22    49.1 1784.65    81.8 1789.18     108 1790.56
   147.3 1788.22   219.3 1771.04   340.4 1750.88   402.6 1735.35   425.6 1733.11
   497.6 1733.03  524.981728.115   530.3  1727.6   540.1 1728.13     563 1732.35
   618.7  1732.9   631.8 1738.55  643.171739.338   654.7 1741.16   664.5 1755.12
  674.711759.509   706.9 1773.32   726.5 1784.82   746.1 1799.47   765.7 1808.17
   827.8 1819.74  871.511823.255  910.831824.946  966.58 1834.61  1007.3 1838.38
#Mann= 8 ,-1 , 0
       0     .12       0  524.98    .045       0   540.1     .12       0
  643.17    .016       0  674.71     .12       0  871.51     .08       0
  910.83     .06       0  966.58     .12       0
#XS Ineff= 2 , 0
          494.29 1734.25
Permanent Ineff=
       F       F
Bank Sta=524.98,540.1
XS Rating Curve= 0 ,0
Exp/Cntr=0.3,0.1

Type RM Length L Ch R = 1 ,9104.2  ,39.1,36.5,36.6
XS GIS Cut Line= 2
      2072910.27      204330.142     2073015.739      205280.663
#Sta/Elev= 30
       0 1796.06    26.2 1788.67    78.6 1764.19   104.8  1756.7   157.2 1750.86
   203.1 1747.94     226 1749.35   245.6 1754.29   278.4 1746.33   376.6 1736.92
   399.6 1731.05   419.2 1730.56     488  1723.6   494.6 1723.31  501.971723.604
   527.3 1728.03  582.621731.577   602.6  1732.4  611.211736.969     619 1741.44
  630.73 1745.38   638.7 1747.74   668.1 1748.89     678 1747.34  686.861751.453
   700.9 1759.58   772.9  1792.9     786 1795.98   838.4 1802.92   956.4 1827.46
#Mann= 7 ,-1 , 0
       0     .12       0     488    .045       0  501.97     .12       0
  582.62    .016       0  611.21     .12       0  630.73    .016       0
  686.86     .12       0
Bank Sta=488,501.97
XS Rating Curve= 0 ,0
Exp/Cntr=0.3,0.1

Type RM Length L Ch R = 1 ,9067.6  ,407.4,412.5,414.8
XS GIS Cut Line= 2
     2072875.114      204339.257     2072980.583      205289.778
#Sta/Elev= 30
       0  1783.9    16.4 1778.75    42.6 1767.94    55.7 1765.01    88.4 1764.62
   108.1 1760.96   147.4 1758.04   222.7 1756.43   271.8 1747.13   334.1 1740.34
   350.4 1739.82   422.5 1727.64   445.4 1727.02   480.9  1723.6   484.7 1723.15
   495.9 1723.61   507.6  1725.7  578.221731.417   602.6 1732.18   609.2 1734.79
     619 1736.22   628.8 1740.96   645.2 1743.08  663.471750.859   687.8  1765.5
   720.5 1778.34   743.5 1790.09   753.3 1793.58   828.6 1804.71   956.4 1832.36
#Mann= 5 ,-1 , 0
       0     .12       0   480.9    .045       0   495.9     .12       0
  578.22    .016       0  663.47     .12       0
#XS Ineff= 2 , 0
          435.17 1729.39  513.38         1729.12
Permanent Ineff=
       F       F
Bank Sta=480.9,495.9
XS Rating Curve= 0 ,0
Exp/Cntr=0.3,0.1

Type RM Length L Ch R = 1 ,8655.2  ,340.8,350,358.6
XS GIS Cut Line= 3
     2072579.552      204312.064     2072535.636      204757.951
     2072529.007      205251.499
#Sta/Elev= 30
       0 1821.81    29.4 1816.33    78.5 1810.83   104.6 1810.82   150.4 1815.34
   176.6 1814.95   232.2 1808.22   264.9  1802.4   307.4 1787.29   340.1 1765.51
   382.6 1740.75   402.3 1732.91   418.6 1729.49   428.4 1720.58   440.5 1717.74
     448 1717.56   457.8 1717.64   470.9 1719.91   601.7 1721.64   611.5 1724.93
  629.83 1734.21   637.6 1738.42     654 1740.19  668.091750.009   709.6  1764.6
  783.971784.482   801.1 1789.03   882.8 1805.04  933.091810.205   941.6 1810.89
#Mann= 7 ,-1 , 0
       0     .12       0   440.5    .045       0   457.8     .12       0
  629.83    .016       0  668.09     .12       0  783.97     .06       0
  933.09     .12       0
Bank Sta=440.5,457.8
XS Rating Curve= 0 ,0
Exp/Cntr=0.3,0.1

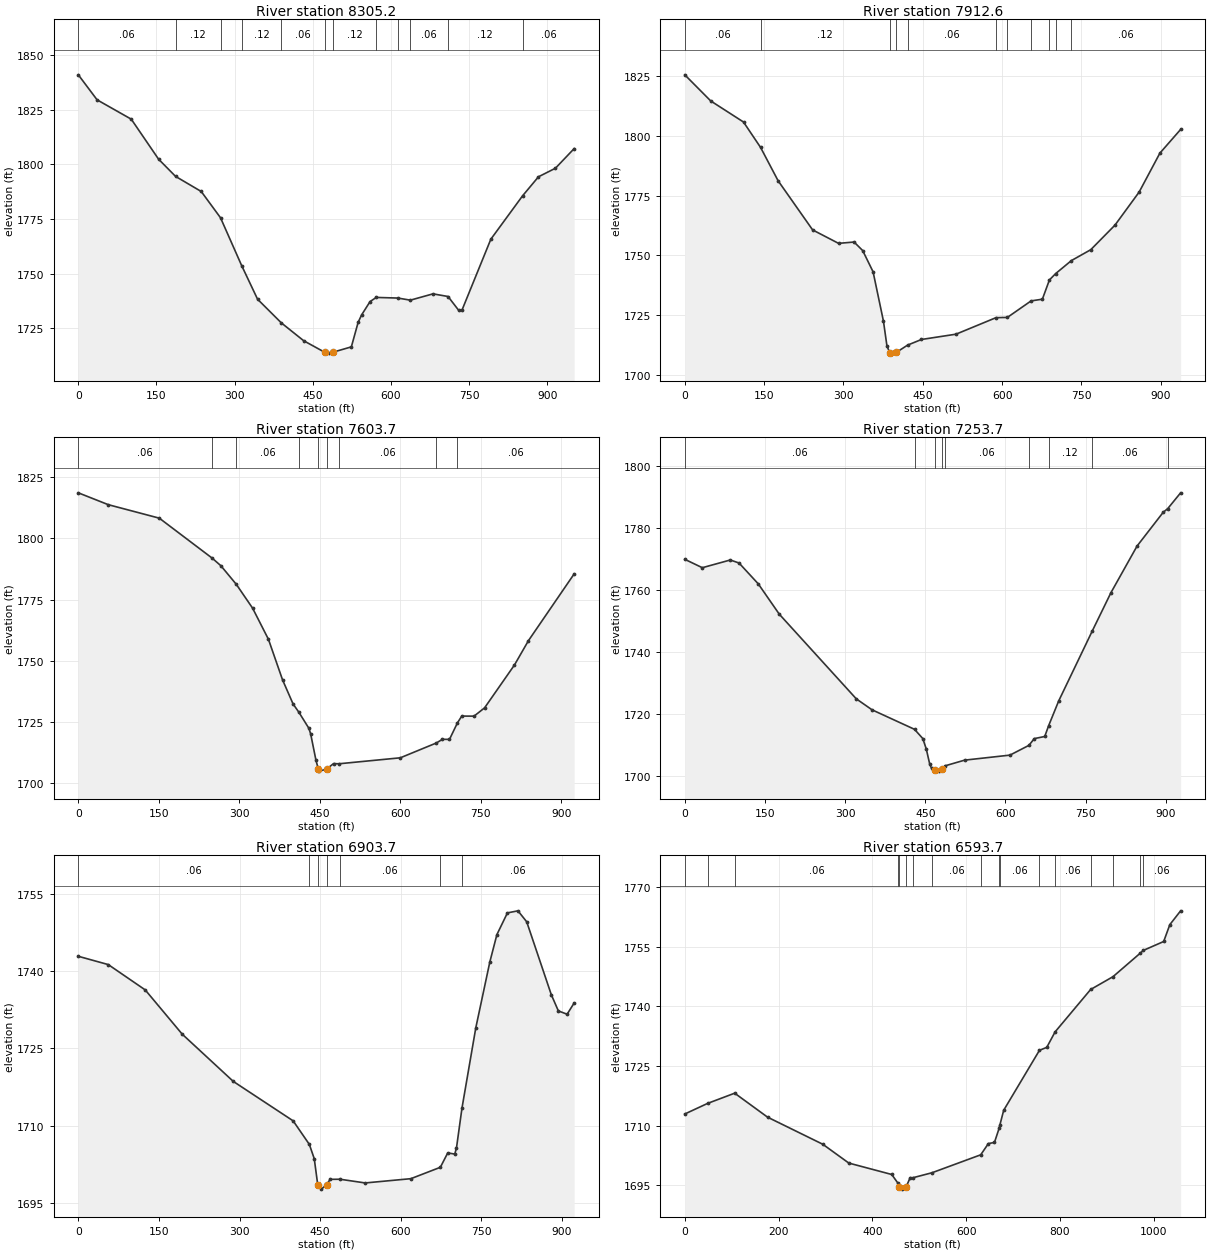
Type RM Length L Ch R = 1 ,8305.2  ,408.6,392.6,369.7
XS GIS Cut Line= 3
     2072401.781      204301.969     2072243.265      204756.676
     2072030.486      205175.873
#Sta/Elev= 30
       0 1840.89      36 1829.46   101.6 1820.62     154 1802.34   186.61794.478
   235.9 1787.57  272.891775.564  313.471753.699     344 1738.34  389.641727.518
   432.4 1719.38  472.971714.078   481.6  1713.7   488.1 1714.08     524 1716.56
     537 1727.76   543.6 1731.14   559.9 1737.26  571.771739.155  613.241738.872
  637.211737.906   680.7 1740.79  709.581739.578   729.7 1733.35   736.2 1733.29
   791.7 1765.77  852.591785.587   883.1 1794.29   915.7 1798.21   951.6 1807.18
#Mann= 12 ,-1 , 0
       0     .06       0   186.6     .12       0  272.89     .06       0
  313.47     .12       0  389.64     .06       0  472.97    .045       0
   488.1     .12       0  571.77     .06       0  613.24    .016       0
  637.21     .06       0  709.58     .12       0  852.59     .06       0
Bank Sta=472.97,488.1
XS Rating Curve= 0 ,0
Exp/Cntr=0.3,0.1

Type RM Length L Ch R = 1 ,7912.6  ,304.5,308.9,306.6
XS GIS Cut Line= 3
     2071782.927      204275.267     2072029.454      204841.239
     2072008.621      205160.684
#Sta/Elev= 30
       0  1825.6      49 1814.66     111 1805.82  143.34 1795.15   176.4 1781.21
   241.7  1760.6   290.7 1754.97   320.1 1755.52   336.4 1751.93     356 1743.04
   375.6 1722.38   382.2 1712.01  387.311709.212     392 1708.96  399.661709.228
  421.321712.324   447.5 1714.68   512.8  1716.9  588.451723.825  609.891723.922
  654.751730.845   676.1 1731.57  689.471739.651  701.291742.309  730.891747.734
   767.6 1752.31   813.3 1762.59   859.1 1776.48   898.3 1792.78   937.5 1802.71
#Mann= 11 ,-1 , 0
       0     .06       0  143.34     .12       0  387.31    .045       0
  399.66     .12       0  421.32     .06       0  588.45     .12       0
  609.89     .06       0  654.75    .016       0  689.47     .08       0
  701.29     .12       0  730.89     .06       0
Bank Sta=387.31,399.66
XS Rating Curve= 0 ,0
Exp/Cntr=0.3,0.1

Type RM Length L Ch R = 1 ,7603.7  ,352.1,350,347
XS GIS Cut Line= 3
     2071529.069      204315.768     2071660.451      204748.874
     2071856.026      205177.606
#Sta/Elev= 30
       0  1818.6    55.8 1813.76   150.9 1808.25  249.461791.909   265.6 1788.82
  294.371781.216   324.7 1771.49   354.2 1758.78   380.4 1742.27   400.1 1732.37
  410.881728.998   429.6 1722.41   432.9 1720.11   442.8 1709.32  447.271705.715
   449.3 1704.94   462.4 1705.76   475.5 1708.01  485.361707.938   599.9 1710.38
  667.181716.445   678.4 1717.94   691.5  1717.9  706.441724.693   714.4 1727.42
   737.3  1727.4   756.9 1730.78   812.6  1748.3   838.7 1758.25   923.8 1785.49
#Mann= 9 ,-1 , 0
       0     .06       0  249.46     .12       0  294.37     .06       0
  410.88     .12       0  447.27    .045       0   462.4     .12       0
  485.36     .06       0  667.18    .016       0  706.44     .06       0
Bank Sta=447.27,462.4
XS Rating Curve= 0 ,0
Exp/Cntr=0.3,0.1

Type RM Length L Ch R = 1 ,7253.7  ,347.6,350,356.9
XS GIS Cut Line= 3
      2071163.53      204472.199     2071370.072      204899.758
     2071616.041      205280.192
#Sta/Elev= 30
       0 1769.88    32.8 1767.17    85.1 1769.66   101.5 1768.69   137.5 1761.95
   176.8 1752.16   320.9 1724.81   350.4 1721.26  429.931714.955   445.4 1711.97
   451.9  1708.6   458.5 1703.62   461.7  1702.4   467.3 1701.95   474.8 1701.45
   481.4 1702.03  487.511703.185   523.7    1705   608.5 1706.62  643.941709.767
   654.1 1711.96   673.6 1712.64  680.751716.059   699.7 1724.12  762.241746.615
   797.5  1759.1   846.4 1774.17   895.3 1785.07  903.781786.258   927.9 1791.36
#Mann= 9 ,-1 , 0
       0     .06       0  429.93     .12       0   467.3    .045       0
   481.4     .12       0  487.51     .06       0  643.94    .016       0
  680.75     .12       0  762.24     .06       0  903.78     .08       0
Bank Sta=467.3,481.4
XS Rating Curve= 0 ,0
Exp/Cntr=0.3,0.1

Type RM Length L Ch R = 1 ,6903.7  ,307.2,310,308.3
XS GIS Cut Line= 3
     2070878.199      204538.135     2071040.826      204960.101
     2071153.116      205417.052
#Sta/Elev= 30
       0 1742.88    55.7 1741.27   124.5 1736.35   193.3 1727.76   288.4 1718.58
   399.8 1710.92   429.91706.354   439.1 1703.57   445.7  1698.4   452.2 1697.66
     462  1698.5   468.6 1699.56  487.13 1699.58   533.9 1698.86   618.9 1699.69
  673.781701.901   687.5 1704.69   700.6 1704.47   703.8 1705.67  714.011713.388
   739.8 1729.02   765.9  1741.8     779 1747.09   798.6 1751.31   818.2 1751.71
   834.5 1749.58   880.3 1735.41   893.4 1732.27   909.7 1731.63   922.8 1733.82
#Mann= 7 ,-1 , 0
       0     .06       0   429.9     .12       0   445.7    .045       0
     462     .12       0  487.13     .06       0  673.78    .016       0
  714.01     .06       0
Bank Sta=445.7,462
XS Rating Curve= 0 ,0
Exp/Cntr=0.3,0.1

Type RM Length L Ch R = 1 ,6593.7  ,313.1,311.9,309
XS GIS Cut Line= 3
     2070637.093      204634.642     2070826.329      205297.836
     2071013.829      205613.809
#Sta/Elev= 30
       0 1712.93    48.71715.596  106.351718.162   176.5 1712.13   294.2 1705.32
   349.7 1700.59   441.2 1697.72  454.611695.502  457.121694.627   464.1 1694.04
  471.94 1694.63   480.5 1696.92   486.2  1696.9  527.041698.158  630.911702.669
   647.2 1705.49   660.2 1705.78  670.541709.474  671.621710.103   679.9 1713.87
  756.141728.942   771.7 1729.68  789.46 1733.57  865.221744.231  912.921747.453
   970.8 1753.34  977.38 1754.05    1021  1756.3  1034.1 1760.54  1057.1 1764.01
#Mann= 17 ,-1 , 0
       0    .016       0    48.7     .12       0  106.35     .06       0
  454.61    .016       0  457.12    .045       0  471.94     .12       0
   486.2    .016       0  527.04     .06       0  630.91    .016       0
  670.54     .12       0  671.62     .06       0  756.14    .016       0
  789.46     .06       0  865.22    .016       0  912.92     .06       0
   970.8     .12       0  977.38     .06       0
Bank Sta=457.12,471.94
XS Rating Curve= 0 ,0
Exp/Cntr=0.3,0.1

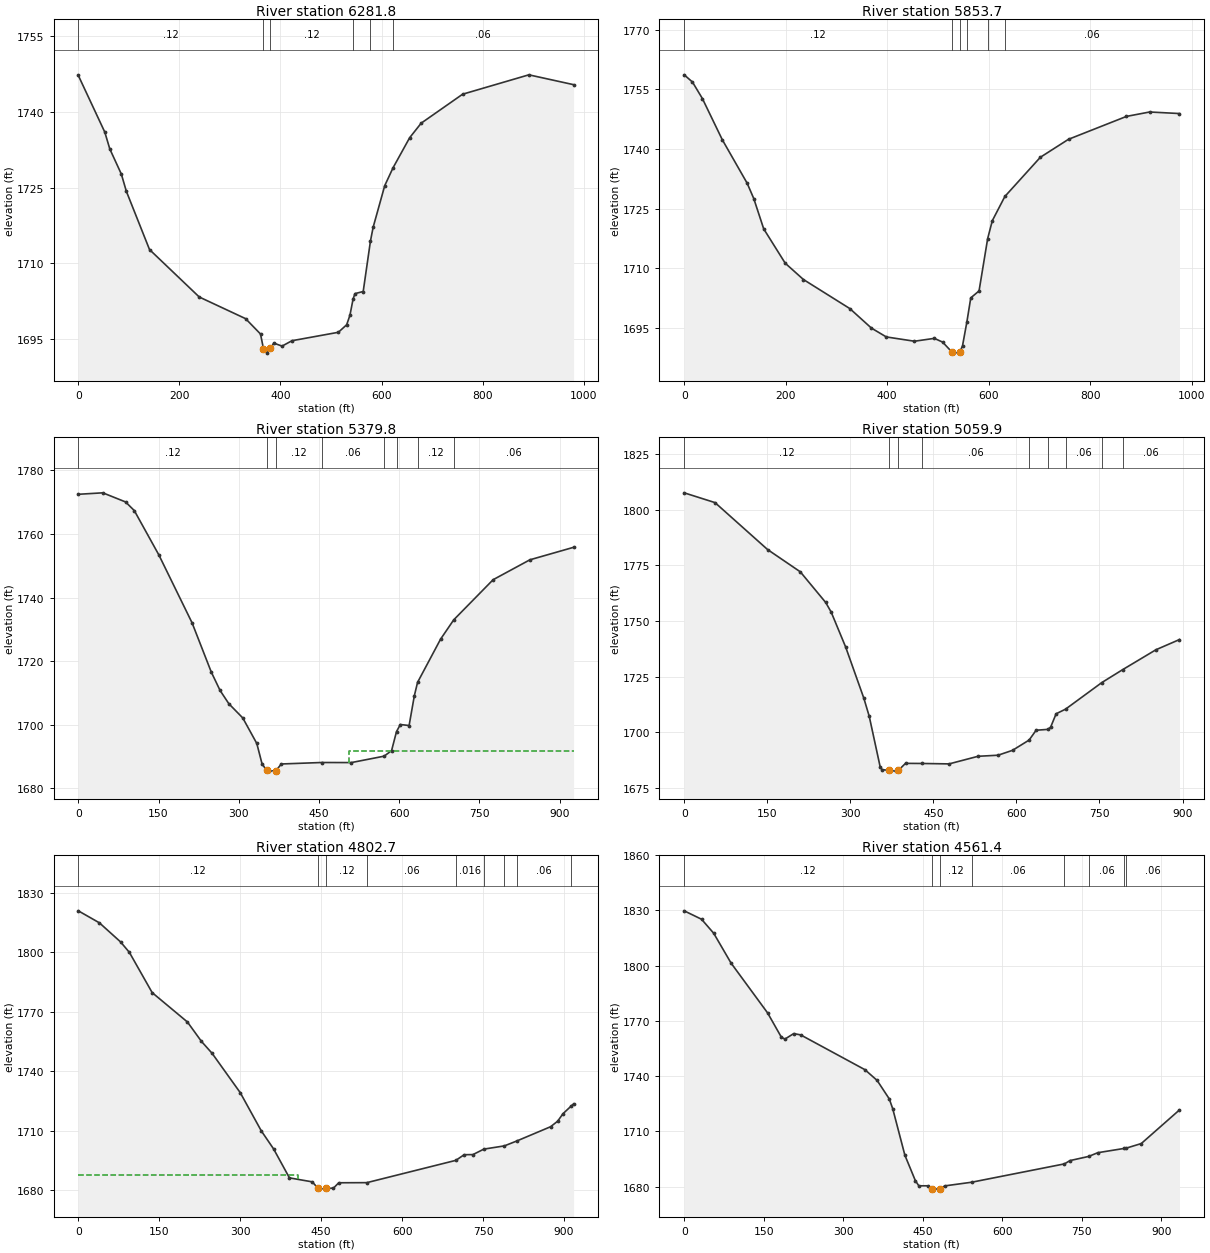
Type RM Length L Ch R = 1 ,6281.8  ,420.3,428.1,427.3
XS GIS Cut Line= 2
     2070359.316      204740.545     2070671.816      205669.364
#Sta/Elev= 30
       0 1747.25    52.4 1736.02    62.3 1732.69    85.2 1727.69      95 1724.31
   140.9 1712.75   239.3 1703.35     331 1699.06   360.5 1696.02  366.411693.088
   373.6 1692.23   380.2 1693.17   386.8 1694.22   403.1 1693.62   422.8 1694.69
   514.6 1696.36     531 1697.85   537.5 1699.75  543.681702.945   547.4 1704.02
   563.7 1704.44  578.071714.452   583.4 1717.18   606.3 1725.41  622.651728.932
   655.5 1734.89   678.4 1737.79   760.4 1743.53   891.5 1747.37     980 1745.42
#Mann= 6 ,-1 , 0
       0     .12       0  366.41    .045       0   380.2     .12       0
  543.68    .016       0  578.07     .12       0  622.65     .06       0
Bank Sta=366.41,380.2
XS Rating Curve= 0 ,0
Exp/Cntr=0.3,0.1

Type RM Length L Ch R = 1 ,5853.7  ,472.2,473.9,479.1
XS GIS Cut Line= 3
     2070086.846      204795.212     2070145.286       205327.41
     2070273.215      205749.136
#Sta/Elev= 30
       0 1758.65    16.3 1756.84    35.9 1752.68    75.1 1742.34   124.1 1731.41
   137.1 1727.56   156.7 1719.94   199.1 1711.31     235 1707.21   326.5  1699.9
   368.9 1695.01   398.3 1692.78   453.8  1691.7     493 1692.42   509.3 1691.48
   527.9 1688.95   541.9 1688.71   542.9 1688.88   548.5 1690.54  557.061696.512
   564.8  1702.6   581.1 1704.34  598.071717.484   607.2 1721.98  631.961728.077
   701.9 1737.93   757.4 1742.45   871.6  1748.2   917.3 1749.31   976.1 1748.92
#Mann= 6 ,-1 , 0
       0     .12       0   527.9    .045       0   542.9     .12       0
  557.06    .016       0  598.07     .12       0  631.96     .06       0
Bank Sta=527.9,542.9
XS Rating Curve= 0 ,0
Exp/Cntr=0.3,0.1

Type RM Length L Ch R = 1 ,5379.8  ,328.8,319.9,310.3
XS GIS Cut Line= 2
     2069779.454      204830.822     2069819.385       205756.17
#Sta/Elev= 30
       0 1772.51    45.8 1772.97    88.4  1770.1   104.7 1767.38   150.6 1753.43
   212.7 1732.06   248.7 1716.53   265.1 1710.76   281.5 1706.58   307.6 1702.09
   333.8 1694.06   343.6 1687.65  352.361685.559   356.7 1685.36   369.8 1685.53
   379.6 1687.61   455.11688.076   510.6 1688.05  571.86 1690.07   585.8 1691.81
  595.031697.801   602.2 1700.03   618.6 1699.72   628.4 1709.11  634.411713.305
   677.5 1726.92  702.081732.992   775.7 1745.62   844.4 1751.88   926.2 1755.82
#Mann= 8 ,-1 , 0
       0     .12       0  352.36    .045       0   369.8     .12       0
   455.1     .06       0  571.86     .12       0  595.03    .016       0
  634.41     .12       0  702.08     .06       0
#XS Ineff= 2 , 0
                          506.75         1691.77
Permanent Ineff=
       F       F
Bank Sta=352.36,369.8
XS Rating Curve= 0 ,0
Exp/Cntr=0.3,0.1

Type RM Length L Ch R = 1 ,5059.9  ,258.9,257.2,254.4
XS GIS Cut Line= 2
     2069322.857      204926.309     2069715.218      205730.128
#Sta/Elev= 30
       0 1807.57    55.7 1803.17   150.7 1782.06   209.7 1772.07   255.6 1758.28
   265.4    1754   291.6 1738.28   324.4  1715.3   334.2 1707.12   353.9 1684.46
   357.1 1683.18   370.2 1682.79   383.3 1682.49   386.6 1682.78   399.7 1685.98
  430.341685.929   478.4 1685.74   530.8 1689.16   566.8 1689.64     593 1691.84
  622.941696.454   635.6 1700.87  656.941701.255   661.8 1702.25   671.7 1708.26
  688.681710.335  754.421722.322   791.61728.057   851.9 1737.03   894.5 1741.63
#Mann= 9 ,-1 , 0
       0     .12       0   370.2    .045       0   386.6     .12       0
  430.34     .06       0  622.94    .016       0  656.94     .12       0
  688.68     .06       0  754.42     .12       0   791.6     .06       0
Bank Sta=370.2,386.6
XS Rating Curve= 0 ,0
Exp/Cntr=0.3,0.1

Type RM Length L Ch R = 1 ,4802.7  ,235.7,241.3,245.5
XS GIS Cut Line= 3
     2069029.368      204996.126     2069268.821      205388.564
     2069511.464      205776.931
#Sta/Elev= 30
       0 1820.84    39.1 1814.78    78.2 1805.19    94.6  1799.9   136.9 1779.57
   202.2 1764.76   228.2 1754.97   247.8    1749     300 1729.14   339.1 1709.82
   361.9 1700.72   391.2 1686.14   433.6 1684.12  444.341680.795   446.7 1680.46
   459.7 1680.82   472.8 1680.98   482.6 1683.67  534.621683.727  699.571694.977
   714.9 1697.82   731.2 1697.88  751.381700.639  789.44 1702.27  812.431704.745
   875.1 1711.94   888.2 1714.74     898 1718.49  913.74 1722.51   917.7 1723.46
#Mann= 9 ,-1 , 0
       0     .12       0  444.34    .045       0   459.7     .12       0
  534.62     .06       0  699.57    .016       0  751.38     .06       0
  789.44     .12       0  812.43     .06       0  913.74     .12       0
#XS Ineff= 2 , 0
          406.17 1687.79
Permanent Ineff=
       F       F
Bank Sta=444.34,459.7
XS Rating Curve= 0 ,0
Exp/Cntr=0.3,0.1

Type RM Length L Ch R = 1 ,4561.4  ,449.2,460.3,468.5
XS GIS Cut Line= 2
      2068897.51      205040.892     2069206.538      205922.836
#Sta/Elev= 30
       0 1829.78    32.8  1825.2    55.7 1817.59    88.5 1801.37   157.4 1774.31
   183.6    1761   190.2 1760.13   206.6 1763.08   219.7 1762.39     341 1743.48
     364 1737.66   386.9 1727.63   393.5 1722.24   416.4 1697.02   436.1 1683.24
   442.7 1680.39   459.1  1680.4   467.2 1678.88   478.7 1678.59   482.2 1678.73
   491.8 1680.35  542.521682.344  717.461692.302   727.9 1694.09  763.041696.347
   780.4 1698.38  830.461700.716   834.1 1700.86   862.4 1703.35   934.5 1721.62
#Mann= 8 ,-1 , 0
       0     .12       0   467.2    .045       0   482.2     .12       0
  542.52     .06       0  717.46    .016       0  763.04     .06       0
  830.46     .12       0   834.1     .06       0
Bank Sta=467.2,482.2
XS Rating Curve= 0 ,0
Exp/Cntr=0.3,0.1

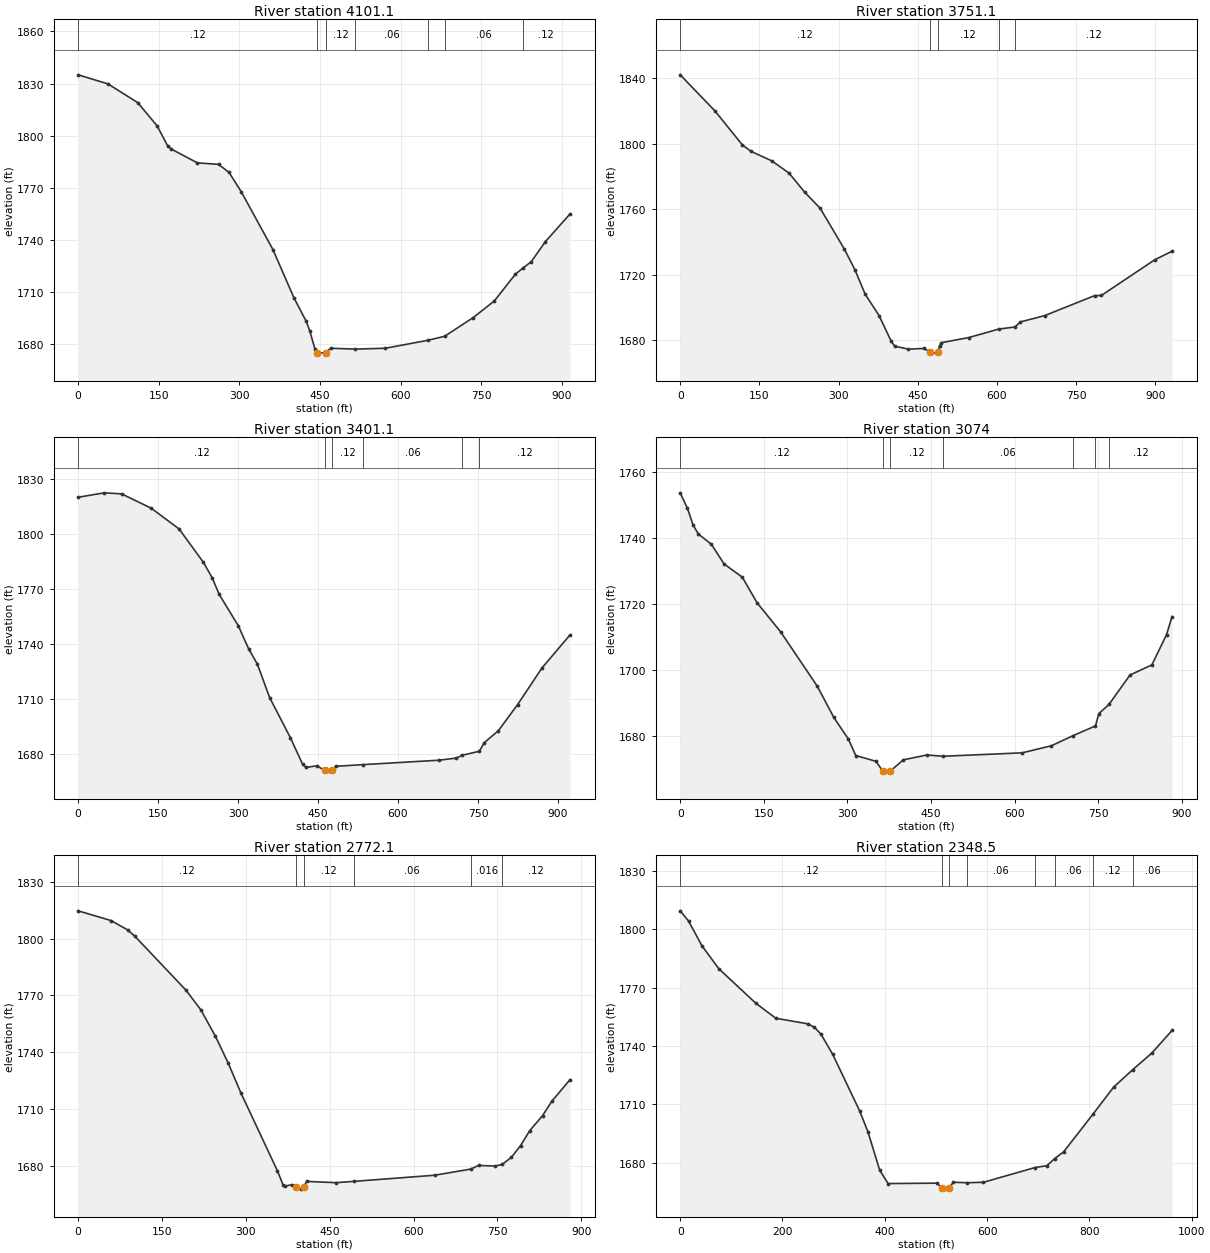
Type RM Length L Ch R = 1 ,4101.1  ,345.5,350,350.9
XS GIS Cut Line= 3
     2068665.632      204984.139     2068621.153      205435.736
     2068584.196      205895.562
#Sta/Elev= 30
       0 1835.04    55.5 1829.82     111    1819   146.9 1805.67   166.5 1794.18
     173 1792.33     222  1784.3   261.2 1783.48   280.8 1778.83   303.6 1767.63
   362.4  1734.4   401.6 1706.56   424.4 1693.05   430.9 1687.66   440.7    1677
  445.25 1675.02   447.2 1674.73   460.3    1675   470.1 1677.53  516.041677.042
   571.6 1677.54  650.76 1682.12  682.081684.443   735.2 1695.24   774.4 1704.78
   813.7 1720.24  826.881723.545   843.1 1727.38   869.3 1738.94   915.1 1754.86
#Mann= 7 ,-1 , 0
       0     .12       0  445.25    .045       0   460.3     .12       0
  516.04     .06       0  650.76    .016       0  682.08     .06       0
  826.88     .12       0
Bank Sta=445.25,460.3
XS Rating Curve= 0 ,0
Exp/Cntr=0.3,0.1

Type RM Length L Ch R = 1 ,3751.1  ,343.7,350,353.5
XS GIS Cut Line= 3
     2068413.403      204962.191     2068284.851      205426.222
     2068182.633       205864.61
#Sta/Elev= 30
       0 1842.18    65.5 1820.26   117.9 1799.35   134.3 1795.42   173.6 1789.64
   206.4 1782.11   235.8 1770.52   265.3 1760.63   311.2 1735.66   330.8 1723.28
   350.5 1708.21   376.7 1695.19   399.6 1679.61   406.2 1676.51   432.4 1674.68
   461.9  1675.1  473.171672.928   484.8 1672.25     488 1672.88   491.3 1676.61
   494.6 1678.61   546.8 1681.76   603.61686.937  633.931688.218   644.6 1691.31
   690.3 1695.14   784.9 1707.34   797.9 1707.47     899 1729.24   931.7 1734.48
#Mann= 5 ,-1 , 0
       0     .12       0  473.17    .045       0     488     .12       0
   603.6    .016       0  633.93     .12       0
Bank Sta=473.17,488
XS Rating Curve= 0 ,0
Exp/Cntr=0.3,0.1

Type RM Length L Ch R = 1 ,3401.1  ,327.6,327,323.2
XS GIS Cut Line= 3
     2068169.403      204883.467     2067978.663      205313.196
     2067808.107      205732.138
#Sta/Elev= 30
       0 1819.88      49  1822.3    81.6 1821.73   137.1 1813.91   189.4  1802.6
   235.1 1784.36   251.4 1776.01   264.5 1766.96   300.4 1749.84     320 1737.15
   336.3 1728.86   359.2 1710.67   398.3  1688.7   421.2 1674.22   427.7 1672.57
   447.3 1673.47   462.7 1671.03   470.2 1670.57   476.7 1671.31   483.3  1673.2
  534.82 1674.12   676.7 1676.52   709.4 1677.68  720.551679.249  752.451681.376
   761.9 1686.12   788.1 1692.56   824.2 1706.81     870 1726.79   922.5  1744.8
#Mann= 6 ,-1 , 0
       0     .12       0   462.7    .045       0   476.7     .12       0
  534.82     .06       0  720.55    .016       0  752.45     .12       0
Bank Sta=462.7,476.7
XS Rating Curve= 0 ,0
Exp/Cntr=0.3,0.1

Type RM Length L Ch R = 1 ,3074    ,301.9,302,300
XS GIS Cut Line= 2
     2067817.649      204848.184     2067527.718      205681.517
#Sta/Elev= 30
       0 1753.71    13.1 1748.98      23 1743.98    32.8 1741.16    55.8 1738.12
    78.7 1732.13   111.5 1728.09   137.8 1720.37   180.4 1711.47     246 1694.99
   275.5 1685.58   301.8 1678.95   314.9 1673.99     351 1672.24  363.24 1669.32
   364.1 1669.25   377.21669.301   400.2 1672.67   442.8 1674.16  470.561673.758
   613.4  1674.8   665.8 1676.94  705.151680.046  744.931682.965   751.1 1686.71
  769.161689.477   806.9 1698.42   846.2  1701.5   872.5 1710.69   882.3 1716.14
#Mann= 7 ,-1 , 0
       0     .12       0  363.24    .045       0   377.2     .12       0
  470.56     .06       0  705.15    .016       0  744.93     .08       0
  769.16     .12       0
Bank Sta=363.24,377.2
XS Rating Curve= 0 ,0
Exp/Cntr=0.3,0.1

Type RM Length L Ch R = 1 ,2772.1  ,417.5,423.6,425.3
XS GIS Cut Line= 2
     2067532.927      204790.892      2067272.51       205631.17
#Sta/Elev= 30
       0 1814.66    58.9 1809.52    88.3 1804.62   101.4 1801.27     193 1772.72
   219.1 1762.54   245.3 1748.58   268.2  1734.4   291.1 1718.52   356.5 1677.32
   366.3 1670.11   369.5 1669.28   382.6 1670.02   389.2 1668.94     399 1667.68
  403.37 1668.99   408.8 1671.76   461.1 1671.09  492.551671.762   637.7 1675.02
  702.281678.263   716.2 1680.18   745.6 1679.88  758.651680.736   775.1 1684.53
   791.4  1690.7   807.8 1698.58   830.6 1706.44     847 1713.97   879.7 1725.48
#Mann= 6 ,-1 , 0
       0     .12       0   389.2    .045       0  403.37     .12       0
  492.55     .06       0  702.28    .016       0  758.65     .12       0
Bank Sta=389.2,403.37
XS Rating Curve= 0 ,0
Exp/Cntr=0.3,0.1

Type RM Length L Ch R = 1 ,2348.5  ,349.9,350,347.1
XS GIS Cut Line= 3
     2067298.837      204691.208     2067043.757      205141.962
     2066834.593       205533.28
#Sta/Elev= 30
       0  1809.6    16.4 1804.31    42.6 1791.57    75.4 1779.84   147.5 1762.12
   186.8 1754.32   249.1 1751.45   262.2 1749.74   275.4 1746.04   298.3 1735.69
   350.8 1706.64   367.1 1695.86   390.1 1676.05   406.5 1669.21   501.5 1669.43
   511.4 1667.08   517.9 1666.35   525.4 1666.97   534.2 1669.89  561.171669.637
     593 1669.88  693.651677.451   716.9 1678.42  731.841682.011   749.6 1685.52
  807.131704.957   847.4 1718.84  884.591727.796   922.5 1736.46   961.6 1748.03
#Mann= 8 ,-1 , 0
       0     .12       0   511.4    .045       0   525.4     .12       0
  561.17     .06       0  693.65    .016       0  731.84     .06       0
  807.13     .12       0  884.59     .06       0
Bank Sta=511.4,525.4
XS Rating Curve= 0 ,0
Exp/Cntr=0.3,0.1

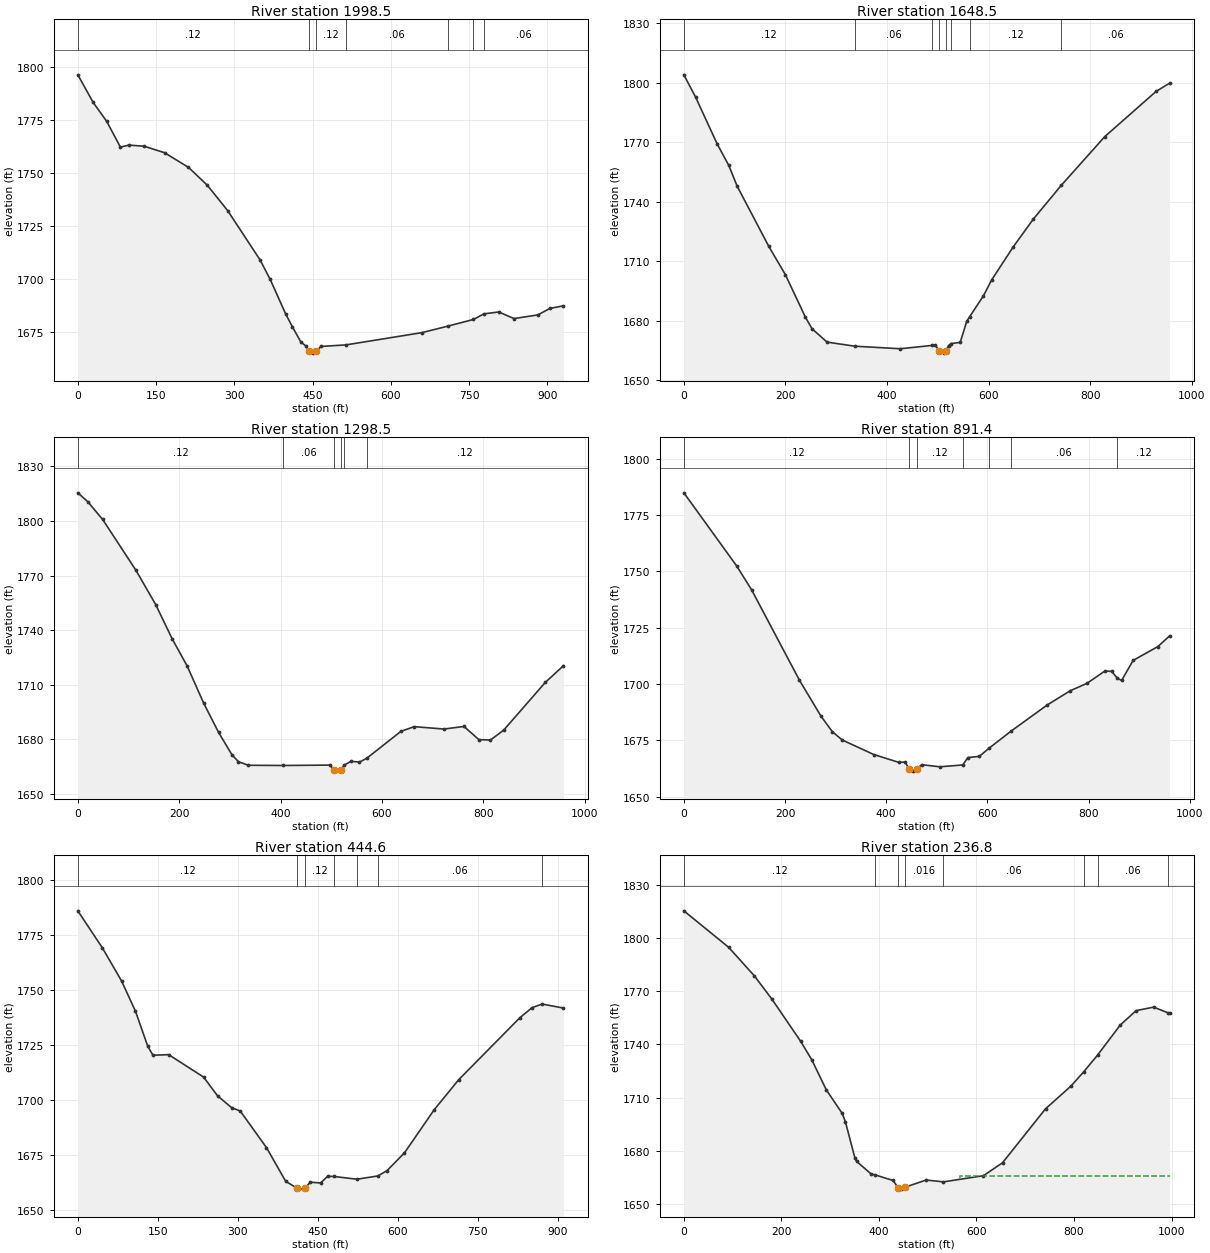
Type RM Length L Ch R = 1 ,1998.5  ,340.1,350,361.1
XS GIS Cut Line= 3
     2067004.868      204513.761     2066819.014      204923.948
     2066612.548      205357.743
#Sta/Elev= 30
       0 1796.22    29.4 1783.23    55.5 1774.27    81.6 1762.18    97.9 1763.13
   127.3  1762.6   166.4 1759.52   212.1 1752.65     248 1744.28   287.2 1732.28
   349.2 1709.11   368.8 1699.85   398.1 1683.76   411.2 1677.59   427.5  1670.4
   437.3  1668.5   442.8 1666.33   450.3 1665.18   456.9 1666.27   466.7 1668.34
  513.651669.048   659.5 1674.83   710.11677.941  758.14 1681.03  778.341683.672
   806.6 1684.56     836 1681.45   881.7 1683.18   904.6 1686.22   930.8 1687.46
#Mann= 7 ,-1 , 0
       0     .12       0   442.8    .045       0   456.9     .12       0
  513.65     .06       0   710.1    .016       0  758.14     .08       0
  778.34     .06       0
Bank Sta=442.8,456.9
XS Rating Curve= 0 ,0
Exp/Cntr=0.3,0.1

Type RM Length L Ch R = 1 ,1648.5  ,337.1,350,359.5
XS GIS Cut Line= 3
     2066845.171      204444.163      2066497.53      204819.277
      2066137.66      205080.979
#Sta/Elev= 30
       0 1803.98      23  1792.8    65.6 1769.14    88.5 1758.28   104.9 1747.87
   167.2 1717.48     200 1703.17   239.3  1681.8   252.4 1675.96   281.9  1669.2
   336.6 1667.15   426.2 1665.86  488.681667.534     495 1667.62  502.811664.959
   511.4 1663.65  516.831664.946   521.2 1667.44  526.191668.484   544.2 1669.07
   557.2 1679.77  562.781681.996     590 1692.57   606.3 1700.65   648.8 1717.29
   688.1 1731.21  743.321748.296   828.8  1772.8   930.2 1795.68   956.4 1799.73
#Mann= 8 ,-1 , 0
       0     .12       0   336.6     .06       0  488.68     .12       0
  502.81    .045       0  516.83     .12       0  526.19    .016       0
  562.78     .12       0  743.32     .06       0
Bank Sta=502.81,516.83
XS Rating Curve= 0 ,0
Exp/Cntr=0.3,0.1

Type RM Length L Ch R = 1 ,1298.5  ,409.8,407.1,391.4
XS GIS Cut Line= 3
     2066793.074      204368.046     2066314.775      204553.461
      2065876.84      204632.481
#Sta/Elev= 30
       0 1815.49    19.6 1810.61      49 1800.84   114.4 1772.98   153.6 1754.03
   186.2 1735.13   215.6 1720.28   248.3  1699.8   277.7  1683.7   303.9 1671.48
   316.9 1667.59   336.5 1665.64  405.471665.528   496.6 1665.74   505.5 1663.26
   509.7 1662.42   519.5 1663.27  525.191665.695   539.2 1667.84   555.5 1667.37
   569.81669.472   637.3 1684.29   663.5 1686.88   722.4 1685.57   761.7 1686.99
   791.1 1679.76     814 1679.51   840.2 1685.01     922 1711.18     958 1720.43
#Mann= 6 ,-1 , 0
       0     .12       0  405.47     .06       0   505.5    .045       0
   519.5     .06       0  525.19    .016       0   569.8     .12       0
Bank Sta=505.5,519.5
XS Rating Curve= 0 ,0
Exp/Cntr=0.3,0.1

Type RM Length L Ch R = 1 ,891.4   ,449.9,446.8,435.9
XS GIS Cut Line= 3
     2066602.371      203934.989     2066104.107      204320.406
     2065774.246      204332.559
#Sta/Elev= 30
       0 1784.79   104.4 1752.37   133.8 1741.82   228.5  1701.7   270.9 1685.82
   293.8 1678.81   313.3 1675.18   375.4 1668.77   424.3 1665.34   437.4 1665.39
  445.411662.355   453.7 1661.41   460.2 1662.38     470 1664.27   505.9 1663.33
  551.251664.142   561.4 1667.41   584.2 1667.97  602.831671.502  646.73 1679.13
   718.2 1690.74   763.9 1697.06   796.6 1700.29   832.6 1705.84   845.6 1705.61
  856.691702.675   865.2 1701.59   888.1  1710.5   937.1 1716.65     960 1721.34
#Mann= 7 ,-1 , 0
       0     .12       0  445.41    .045       0   460.2     .12       0
  551.25    .016       0  602.83     .12       0  646.73     .06       0
  856.69     .12       0
Bank Sta=445.41,460.2
XS Rating Curve= 0 ,0
Exp/Cntr=0.3,0.1

Type RM Length L Ch R = 1 ,444.6   ,236.1,207.8,166.5
XS GIS Cut Line= 2
     2066329.802      203556.517     2065769.038      204273.531
#Sta/Elev= 30
       0 1785.89    45.8 1769.17    81.9 1754.11     108 1740.37     131  1724.5
   140.8 1720.36   170.3 1720.63   235.8 1710.44   261.9 1701.94   288.1 1696.62
   304.5 1695.03   353.6 1678.46   389.6 1663.17   410.8 1660.02   422.4 1659.61
   425.8 1659.93   435.5 1662.77   455.1  1662.4   468.2 1665.44  480.121665.356
  523.331664.109   562.41665.587   579.6 1668.01   612.3 1676.09     668 1695.64
   713.8 1709.24   828.4 1737.35   851.3 1741.95  870.231743.593   910.3 1741.77
#Mann= 7 ,-1 , 0
       0     .12       0   410.8    .045       0   425.8     .12       0
  480.12    .016       0  523.33     .12       0   562.4     .06       0
  870.23     .12       0
Bank Sta=410.8,425.8
XS Rating Curve= 0 ,0
Exp/Cntr=0.3,0.1

Type RM Length L Ch R = 1 ,236.8   ,36,35.8,48
XS GIS Cut Line= 4
     2066161.572      203452.538     2065877.718      203729.882
     2065927.197      203805.403     2065714.958      204267.642
#Sta/Elev= 30
       0 1815.18    91.8 1794.65   144.3 1778.65   180.4 1765.52   239.4 1741.76
   262.4 1731.25   291.9 1714.47   324.7 1701.14   331.3 1696.33   350.9 1675.87
   354.2 1674.13   383.7 1667.11   392.81666.459   429.1 1663.38   438.9 1659.42
   445.2 1658.51   453.9 1659.63   496.9 1663.64  532.171662.601   614.3 1666.08
   653.4 1673.36   741.5 1703.71   793.6  1716.5  820.221724.669  848.291733.987
   894.7 1750.85   927.3 1759.01   963.2 1760.96   992.11757.829   995.8 1757.41
#Mann= 8 ,-1 , 0
       0     .12       0   392.8    .016       0   438.9    .045       0
   453.9    .016       0  532.17     .06       0  820.22     .12       0
  848.29     .06       0   992.1     .12       0
#XS Ineff= 2 , 0
                          566.69         1666.12
Permanent Ineff=
       F       F
Bank Sta=438.9,453.9
XS Rating Curve= 0 ,0
Exp/Cntr=0.3,0.1

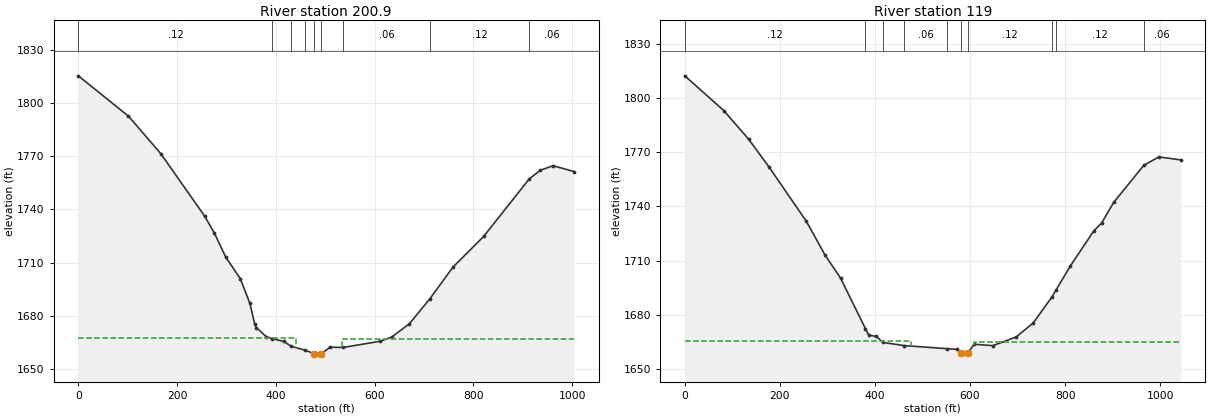
Type RM Length L Ch R = 1 ,200.9   ,72.2,82,90.8
XS GIS Cut Line= 4
     2066155.062      203442.122     2065845.166      203744.205
     2065894.645      203819.726     2065703.239      204261.132
#Sta/Elev= 30
       0 1815.42   101.6 1792.63   167.2 1771.42   255.7 1736.27   275.4 1726.72
   298.4 1713.15   327.9 1700.96   347.5 1686.95   357.4 1675.05   360.6 1673.32
   380.3 1668.21  393.161666.984   416.4 1665.43  431.271662.688  459.331660.502
   477.9 1658.51   487.6 1658.29  492.071658.557   510.2 1662.21  536.281662.061
   611.4 1665.58   634.3 1667.88   670.3 1675.38   711.5 1689.36   758.7 1707.39
   820.9 1724.74  913.141757.186   935.4 1762.07   961.6 1764.67  1004.2 1761.36
#Mann= 9 ,-1 , 0
       0     .12       0  393.16    .016       0  431.27     .06       0
  459.33    .016       0   477.9    .045       0  492.07    .016       0
  536.28     .06       0   711.5     .12       0  913.14     .06       0
#XS Ineff= 2 , 0
          441.06 1667.14  533.18            1667
Permanent Ineff=
       F       F
Bank Sta=477.9,492.07
XS Rating Curve= 0 ,0
Exp/Cntr=0.3,0.1

Type RM Length L Ch R = 1 ,119     ,118.3,119,118.9
XS GIS Cut Line= 4
     2066133.621      203422.836     2065767.302      203658.947
     2065805.496      203877.697     2065697.857      204247.489
#Sta/Elev= 30
       0 1812.25    81.9 1793.07   134.4 1777.18     177  1761.9   255.6 1731.86
   294.9 1713.19   327.7 1700.38  379.981672.463   386.7  1668.9     403 1668.15
   417.31664.818  461.321663.091  551.281661.399     573 1661.02  580.881659.176
     586 1658.37   595.8 1659.23   608.9 1663.82   648.1 1663.07     697 1667.84
     733 1675.62  771.751689.793   781.11693.901   811.3 1707.22   860.2 1726.46
   876.6 1730.83   902.7 1742.43  965.581762.774   997.3 1767.41    1043 1765.77
#Mann= 10 ,-1 , 0
       0     .12       0  379.98    .016       0   417.3     .12       0
  461.32     .06       0  551.28     .12       0  580.88    .045       0
   595.8     .12       0  771.75     .06       0   781.1     .12       0
  965.58     .06       0
#XS Ineff= 2 , 0
             475 1665.81   607.5         1665.25
Permanent Ineff=
       F       F
Bank Sta=580.88,595.8
XS Rating Curve= 0 ,0
Exp/Cntr=0.3,0.1

Chan Stop Cuts=-1
Use User Specified Reach Order=0
Composite Channel Slope=5